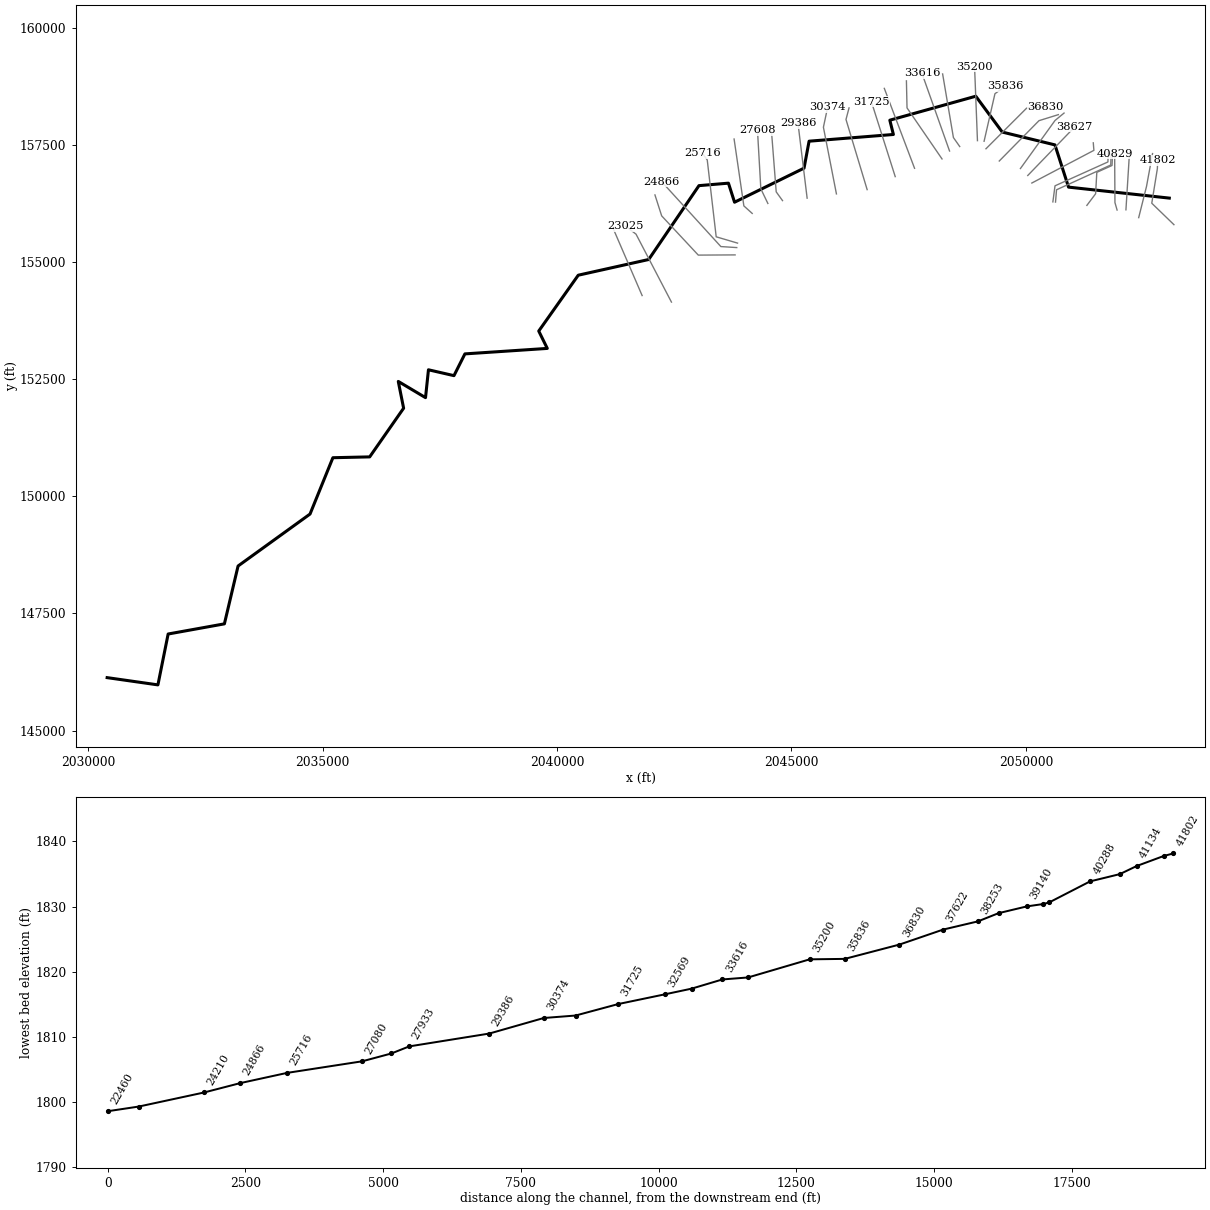
--- RICHCK_A.prj (project) ---

Proj Title=RICHCK_A
Current Plan=p01
Default Exp/Contr=0,0
English Units
Geom File=g01
Flow File=f01
Plan File=p01
Background Map Layer=Inundation Boundary (01pct Value_0)
BEGIN DESCRIPTION:
Stream Name: Rich Creek (Middle Reach)
Flood Zone: Approximate
Hardy County, West Virginia
HEC-RAS Version: 5.0.7
Vertical Datum: NAVD88
Projection: NAD_1983_StatePlane_West_Virginia_North_FIPS_4701_Feet
LiDAR: 2016, 1-meter
Land Use: 2011 WVU NRAC
Hydrologic Method:
SIR2010-5033  Regression
END DESCRIPTION:
DSS Export Rating Curves= 0
DSS Export Rating Curve Sorted= 0
DSS Export Volume Flow Curves= 0
DXF Filename=.\backup\RICHCK.
DXF OffsetX= 0
DXF OffsetY= 0
DXF ScaleX= 0
DXF ScaleY= 0

--- RICHCK_A.p01 (plan) ---

Plan Title=Floodplain
Program Version=5.07
Short Identifier=Floodplain
Geom File=g01
Flow File=f01
Subcritical Flow
K Sum by GR= 0
Std Step Tol= 0.01
Critical Tol= 0.01
Num of Std Step Trials= 20
Max Error Tol= 0.3
Flow Tol Ratio= 0.001
Split Flow NTrial= 30
Split Flow Tol= 0.02
Split Flow Ratio= 0.02
Log Output Level= 0
Friction Slope Method= 1
Unsteady Friction Slope Method= 2
Unsteady Bridges Friction Slope Method= 1
Parabolic Critical Depth
Global Vel Dist= 0 , 0 , 0
Global Log Level= 0
CheckData=True
Encroach Param=-1 ,0,0, 0
Mapping Interval=1HOUR
Computation Time Step Use Courant=        0
Computation Time Step Use Time Series=    0
Computation Time Step Count To Double=0
Computation Time Step Max Doubling=0
Computation Time Step Max Halving=0
Computation Time Step Residence Courant=0
Run HTab= 0
Run UNet= 0
Run Sediment= 0
Run PostProcess= 0
Run WQNet= 0
Run RASMapper=-1
UNET Theta= 0
UNET Theta Warmup= 0
UNET ZTol= 0
UNET ZSATol= 0
UNET MxIter= 0
UNET Max Iter WO Improvement= 0
UNET MaxInSteps= 0
UNET DtIC= 0
UNET DtMin= 0
UNET MaxCRTS= 0
UNET WFStab= 0
UNET SFStab= 0
UNET WFX= 1
UNET SFX= 1
UNET 1D Methodology=Finite Difference
UNET DSS MLevel= 1
UNET Pardiso=0
UNET DZMax Abort= 0
UNET Use Existing IB Tables= 0
UNET Froude Reduction=False
UNET Froude Limit= 0
UNET Froude Power= 0
UNET D1 Cores= 0
UNET D2 Coriolis=0
UNET D2 Cores= 0
UNET D2 Theta= 1
UNET D2 Theta Warmup= 1
UNET D2 Z Tol= 0.01
UNET D2 Volume Tol= 0.01
UNET D2 Max Iterations= 20
UNET D2 Equation= 0
UNET D2 RampUpFraction=0.1
UNET D2 TimeSlices= 1
UNET D2 BCVolumeCheck=0
UNET D1D2 MaxIter= 0
UNET D1D2 ZTol=0.01
UNET D1D2 QTol=0.1
UNET D1D2 MinQTol=1
Write IC File= 0
Write IC File at Fixed DateTime=0
Write IC File at Sim End=0
Echo Input=False
Echo Parameters=False
Echo Output=False
Write Detailed= 0
HDF Write Warmup=0
HDF Write Time Slices=0
HDF Flush=0
HDF Face Node Velocities=0
HDF Compression= 1
HDF Chunk Size= 1
HDF Spatial Parts= 1
HDF Use Max Rows=0
HDF Fixed Rows= 1
Calibration Method= 0
Calibration Iterations= 20
Calibration Max Change=0.05
Calibration Tolerance=0.2
Calibration Maximum=1.5
Calibration Minimum=0.5
Calibration Optimization Method= 1
WQ AD Non Conservative
WQ ULTIMATE=-1
WQ Max Comp Step=1HOUR
WQ Output Interval=15MIN
WQ Output Selected Increments= 0
WQ Output face flow=0
WQ Output face velocity=0
WQ Output face area=0
WQ Output face dispersion=0
WQ Output cell volume=0
WQ Output cell surface area=0
WQ Output cell continuity=0
WQ Output cumulative cell continuity=0
WQ Output face conc=0
WQ Output face dconc_dx=0
WQ Output face courant=0
WQ Output face peclet=0
WQ Output face adv mass=0
WQ Output face disp mass=0
WQ Output cell mass=0
WQ Output cell source sink temp=0
WQ Output nsm pathways=0
WQ Output nsm derived pathways=0
WQ Output MaxMinRange=-1
WQ Daily Max Min Mean=-1
WQ Daily Range=0
WQ Daily Time=0
WQ Create Restart=0
WQ Fixed Restart=0
WQ System Summary=0
WQ Write To DSS=0
WQ Use Fixed Temperature=0
Sorting and Armoring Iterations= 10
XS Update Threshold= 0.02
Bed Roughness Predictor= 0
Hydraulics Update Threshold= 0.02
Energy Slope Method= 1
Volume Change Method= 1
Sediment Retention Method= 0
XS Weighting Method= 0
Number of US Weighted Cross Sections= 1
Number of DS Weighted Cross Sections= 1
Upstream XS Weight=0
Main XS Weight=1
Downstream XS Weight=0
Number of DS XS's Weighted with US Boundary= 1
Upstream Boundary Weight= 1
Weight of XSs Associated with US Boundary= 0
Number of US XS's Weighted with DS Boundary= 1
Downstream Boundary Weight= 0.5
Weight of XSs Associated with DS Boundary= 0.5
Percentile Method= 0
Sediment Output Level= 3
Mass or Volume Output= 0
Output Increment Type= 1
Profile and TS Output Increment= 1
XS Output Flag= 0
XS Output Increment= 10
Write Gradation File= 0
Read Gradation Hotstart= 0
Write HDF5 File= 1
Write Binary Output= 1
Write DSS Sediment File= 0
SV Curve= 0
Specific Gage Flag= 0

--- RICHCK_A.f01 (steady flow) ---

Flow Title=Flow
Program Version=5.07
Number of Profiles= 6
Profile Names=01pct,10pct,04pct,02pct,0_2pct,01plus
River Rch & RM=RickCk_A,Main            ,41802
    2220    1230    1600    1900    3020    3280
River Rch & RM=RickCk_A,Main            ,35836
    2820    1590    2050    2420    3820    4170
River Rch & RM=RickCk_A,Main            ,23025
    3730    2120    2720    3210    5020    5510
River Rch & RM=RickCk_A,Main            ,19288
    4150    2880    3680    4330    6730    7420
Boundary for River Rch & Prof#=RickCk_A,Main            , 1
Up Type= 0
Dn Type= 1
Dn Known WS=1699.5
Boundary for River Rch & Prof#=RickCk_A,Main            , 2
Up Type= 0
Dn Type= 1
Dn Known WS=1698.1
Boundary for River Rch & Prof#=RickCk_A,Main            , 3
Up Type= 0
Dn Type= 1
Dn Known WS=1698.6
Boundary for River Rch & Prof#=RickCk_A,Main            , 4
Up Type= 0
Dn Type= 1
Dn Known WS=1699
Boundary for River Rch & Prof#=RickCk_A,Main            , 5
Up Type= 0
Dn Type= 1
Dn Known WS=1700.3
Boundary for River Rch & Prof#=RickCk_A,Main            , 6
Up Type= 0
Dn Type= 1
Dn Known WS=1700.6
DSS Import GetInterval= 0
DSS Import GetPeak= 0
DSS Import FillOption= 0

--- RICHCK_A.g01 (geometry) ---

Geom Title=Geometry
Program Version=5.07

River Reach=RickCk_A        ,Main
Reach XY= 30
 2053059.9065331 156367.43938947     2050910.591156601.808999989
2050620.13900001157503.5449999842049496.52800001 157777.15599997
2048931.65000001158542.407000014     2047097.816158030.734999986
2047173.83800001157725.7400001042045375.25400002157582.454999967
2045267.60700001157006.7770000042043785.31600002156279.694000019
      2043654.74156686.4520000092043025.94099999156633.513000013
2041953.43000002155056.663000032     2040450.652154721.572000039
2039607.94400001153529.752999993     2039790.235153158.812000001
2038032.68299999153041.9420000172037799.34999999152577.359000009
2037255.22600002152702.5559999942037192.40600001152107.914999994
     2036611.155152454.4420000642036725.30499999151882.356999995
2036001.31700002150843.3019999812035216.42199999150825.594000013
2034728.58599999149622.954999971     2033193.619148514.017999995
2032901.67599999147278.9449999682031701.67600002147062.277999991
     2031483.569145976.265000011 2030400.5596755146130.887497835

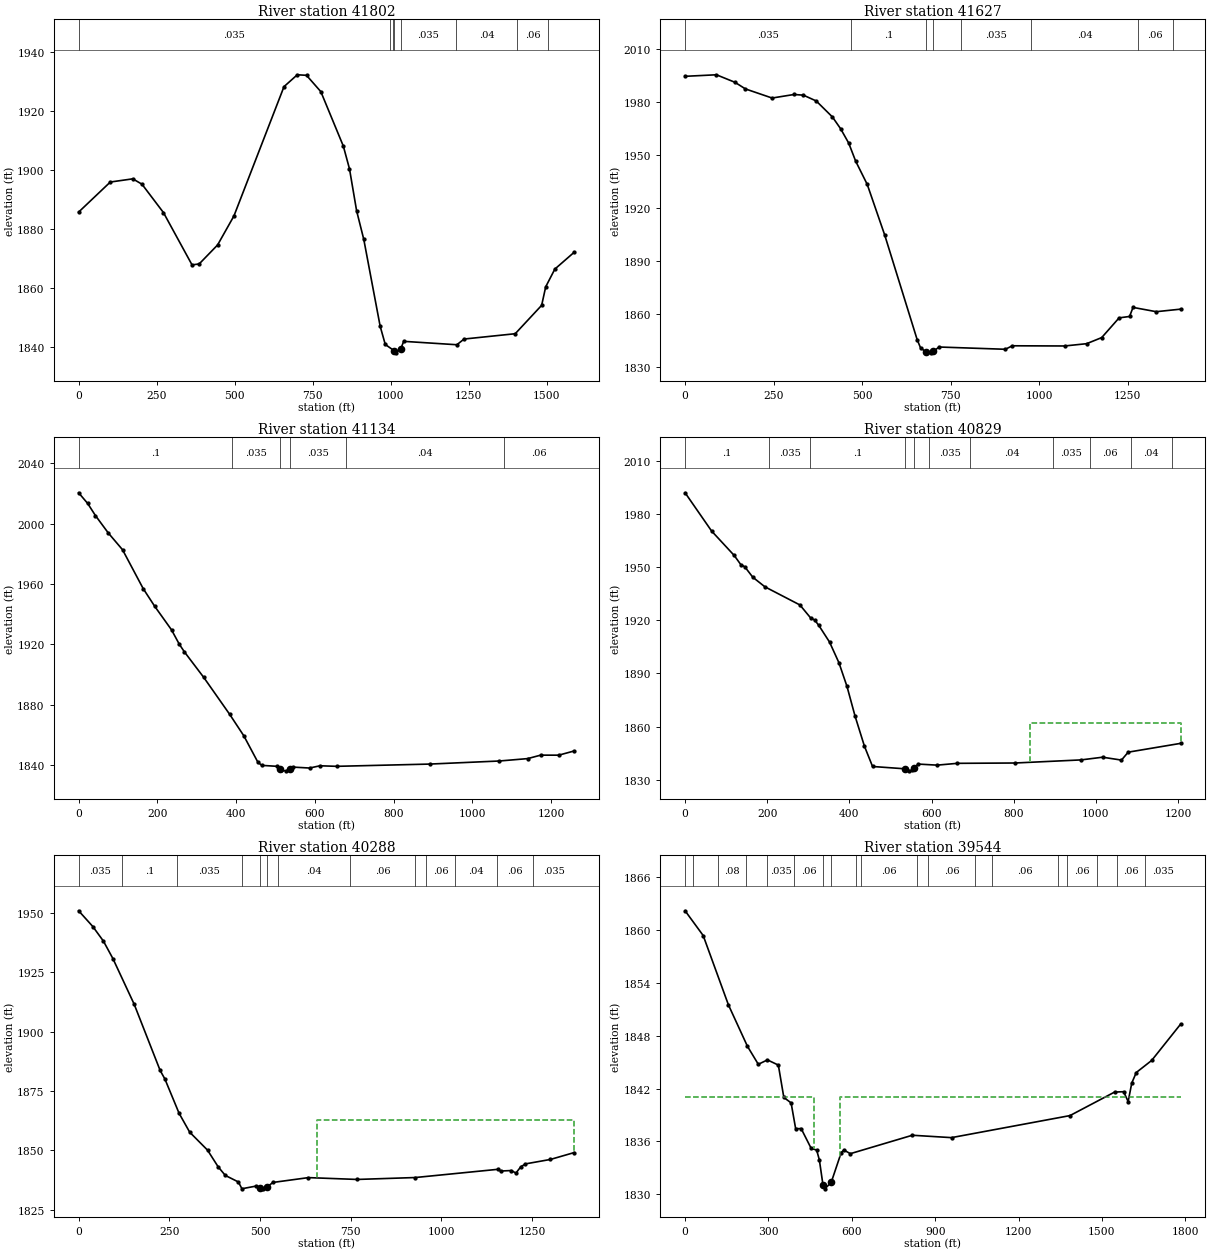
Type RM Length L Ch R = 1 ,41802   ,174.3,174.3,174.3
XS GIS Cut Line= 4
     2053158.787      155800.398     2052686.131      156258.297
     2052805.489      156996.144     2052811.999      157178.436
#Sta/Elev= 30
       0  1885.8   101.5 1895.97   173.5 1897.05     203 1895.23   271.8 1885.63
   363.4 1867.93   386.3 1868.25   445.3 1874.67   497.7  1884.5   658.1 1928.26
   700.7 1932.27   730.2 1932.09   776.1 1926.56   848.2 1908.13   867.9 1900.44
   890.8 1886.21   913.8 1876.52   966.2 1847.16   982.6 1840.99  1011.3 1838.86
  1015.4 1838.16  1031.8 1839.39  1041.6 1842.05  1212.1  1840.9  1235.1 1842.83
    1399 1844.63  1483.7 1854.24  1496.7 1860.51    1526 1866.51  1587.9  1872.2
#Mann= 8 ,-1 , 0
       0    .035       0  998.08      .1       0 1008.08    .035       0
  1011.3    .045       0  1031.8    .035       0 1208.08     .04       0
 1405.52     .06       0 1505.52    .035       0
Bank Sta=1011.3,1031.8
XS Rating Curve= 0 ,0
Exp/Cntr=0.3,0.1

Type RM Length L Ch R = 1 ,41627   ,486.7,493.3,487.2
XS GIS Cut Line= 3
     2052407.044      155950.342     2052574.221      156618.025
      2052702.58      157317.931
#Sta/Elev= 30
       0 1994.61    88.5 1995.48   140.9 1991.21   170.4 1987.46   245.8 1982.29
   308.1 1984.31   334.3 1983.91   370.4 1980.63   416.2 1971.55   439.2 1964.92
   462.1 1956.77   481.8 1946.52   514.6 1933.27   563.8 1904.65   655.5  1845.3
   665.4 1840.48   680.8 1838.34   694.8 1837.77   701.4 1838.68   717.8 1841.07
   904.7 1839.79   924.4 1841.77    1072 1841.66  1134.3 1842.96  1176.9 1846.42
  1226.1 1857.61  1255.6  1858.4  1265.4 1863.54    1331 1861.11  1399.9 1862.55
#Mann= 8 ,-1 , 0
       0    .035       0     470      .1       0   680.8    .045       0
   701.4      .1       0  778.29    .035       0  978.29     .04       0
 1278.29     .06       0 1378.29    .035       0
Bank Sta=680.8,701.4
XS Rating Curve= 0 ,0
Exp/Cntr=0.3,0.1

Type RM Length L Ch R = 1 ,41134   ,301.6,305.2,303.6
XS GIS Cut Line= 2
     2052134.916      156117.238     2052213.041      157373.748
#Sta/Elev= 30
       0 2020.48      23  2013.4    42.6 2005.42    75.4 1993.82   111.5 1982.75
   163.9 1957.02   193.4  1945.2     236 1929.64   255.7 1920.13   268.8 1915.02
     318 1898.08   383.6  1873.7   419.6 1859.46   455.7 1841.78   465.5 1839.84
   504.9  1839.2   511.4 1837.61   514.7 1836.45   527.8 1836.22   537.7 1837.48
   544.2  1838.7   586.8 1838.08   613.1 1839.57   655.7 1839.21   891.8  1840.7
  1068.8 1842.74  1140.9 1844.33  1173.7 1846.62  1219.6  1846.6  1258.9 1849.39
#Mann= 6 ,-1 , 0
       0      .1       0     390    .035       0   511.4    .045       0
   537.7    .035       0     680     .04       0    1080     .06       0
Bank Sta=511.4,537.7
XS Rating Curve= 0 ,0
Exp/Cntr=0.3,0.1

Type RM Length L Ch R = 1 ,40829   ,529.1,540.7,525.4
XS GIS Cut Line= 3
     2051946.114      156112.898     2051900.541      156271.318
      2051894.03      157312.985
#Sta/Elev= 30
       0 1992.12    64.6 1970.48   119.6 1956.69   135.8 1951.47   145.4 1950.27
   164.8 1944.41   194.3 1938.98   279.5 1928.73   305.7 1921.38   315.5 1920.19
   325.4 1917.21   351.6 1907.79   374.5  1896.1   394.2 1882.66   413.8 1865.91
   436.7 1848.87   456.4 1837.44   534.4 1836.14   544.8 1834.98   551.4 1835.21
   557.9 1836.86   567.8  1838.8   613.6  1838.2   662.8 1839.22   803.6 1839.41
   964.1 1841.16  1016.5 1842.68  1062.4 1841.05  1078.8 1845.53  1206.5 1850.51
#Mann= 11 ,-1 , 0
       0      .1       0  204.84    .035       0  304.84      .1       0
   534.4    .045       0   557.9      .1       0  594.84    .035       0
  694.84     .04       0  894.84    .035       0  984.84     .06       0
 1084.84     .04       0 1184.84    .035       0
#XS Ineff= 2 , 0
                          840.47            1862
Permanent Ineff=
       F       F
Bank Sta=534.4,557.9
XS Rating Curve= 0 ,0
Exp/Cntr=0.3,0.1

Type RM Length L Ch R = 1 ,40288   ,737.1,744.3,740.9
XS GIS Cut Line= 5
       2051301.8      156212.507     2051488.003       156459.83
     2051513.605      156917.368     2051838.258       157064.07
     2051848.675      157306.257
#Sta/Elev= 30
       0 1950.79    39.1 1944.17    68.4 1938.02    94.5 1930.69   153.2 1911.48
   224.8 1883.63   237.9 1880.04     277 1865.63   306.3 1857.68   355.4 1850.15
   384.9 1843.09   404.5  1839.5   440.5 1836.75   450.3  1833.9   489.6 1835.03
   499.4 1834.41   509.2 1833.86   519.1  1834.5   535.4 1836.54   633.6 1838.58
   767.8 1837.81     928 1838.61  1156.8 1842.08  1163.4 1841.34  1192.9 1841.56
    1206  1840.5  1219.1 1843.11  1232.2 1844.35    1301 1846.22  1366.5 1849.11
#Mann= 13 ,-1 , 0
       0    .035       0     120      .1       0     270    .035       0
  449.58     .06       0   499.4    .045       0   519.1     .06       0
  549.58     .04       0  749.58     .06       0  927.83    .035       0
  957.83     .06       0 1037.83     .04       0 1154.09     .06       0
 1254.09    .035       0
#XS Ineff= 2 , 0
                          658.24         1862.98
Permanent Ineff=
       F       F
Bank Sta=499.4,519.1
XS Rating Curve= 0 ,0
Exp/Cntr=0.5,0.3

Type RM Length L Ch R = 1 ,39544   ,109.9,101.4,93.9
XS GIS Cut Line= 4
     2050632.746      156282.603     2050654.447      156545.189
     2051811.565      157074.269     2051818.076      157321.665
#Sta/Elev= 30
       0 1862.17    65.1 1859.36   156.1 1851.48   224.4 1846.79   263.5 1844.75
   296.3 1845.25   335.6 1844.66   355.3 1840.99   381.5 1840.37   397.9 1837.44
   417.6 1837.46   453.7 1835.21   473.4 1835.02   483.2  1833.9   496.3 1831.04
   502.9 1830.62   525.8 1831.35   561.9 1834.74   571.7 1835.02   594.7 1834.61
   817.7  1836.7   958.7 1836.43    1385 1838.93  1545.6  1841.6  1578.2 1841.64
  1594.4 1840.52  1607.5 1842.63  1623.7 1843.82  1679.1 1845.19  1783.3 1849.31
#Mann= 19 ,-1 , 0
       0      .1       0      30     .06       0     120     .08       0
     220     .06       0  293.48    .035       0  393.48     .06       0
   496.3    .045       0   525.8     .06       0  613.48    .035       0
  633.48     .06       0  833.48    .035       0  873.48     .06       0
 1043.48    .035       0 1103.48     .06       0 1343.48     .04       0
 1373.48     .06       0 1483.48     .04       0 1555.82     .06       0
 1655.82    .035       0
#XS Ineff= 2 , 0
             465    1841     556            1841
Permanent Ineff=
       F       F
Bank Sta=496.3,525.8
XS Rating Curve= 0 ,0
Exp/Cntr=0.5,0.3

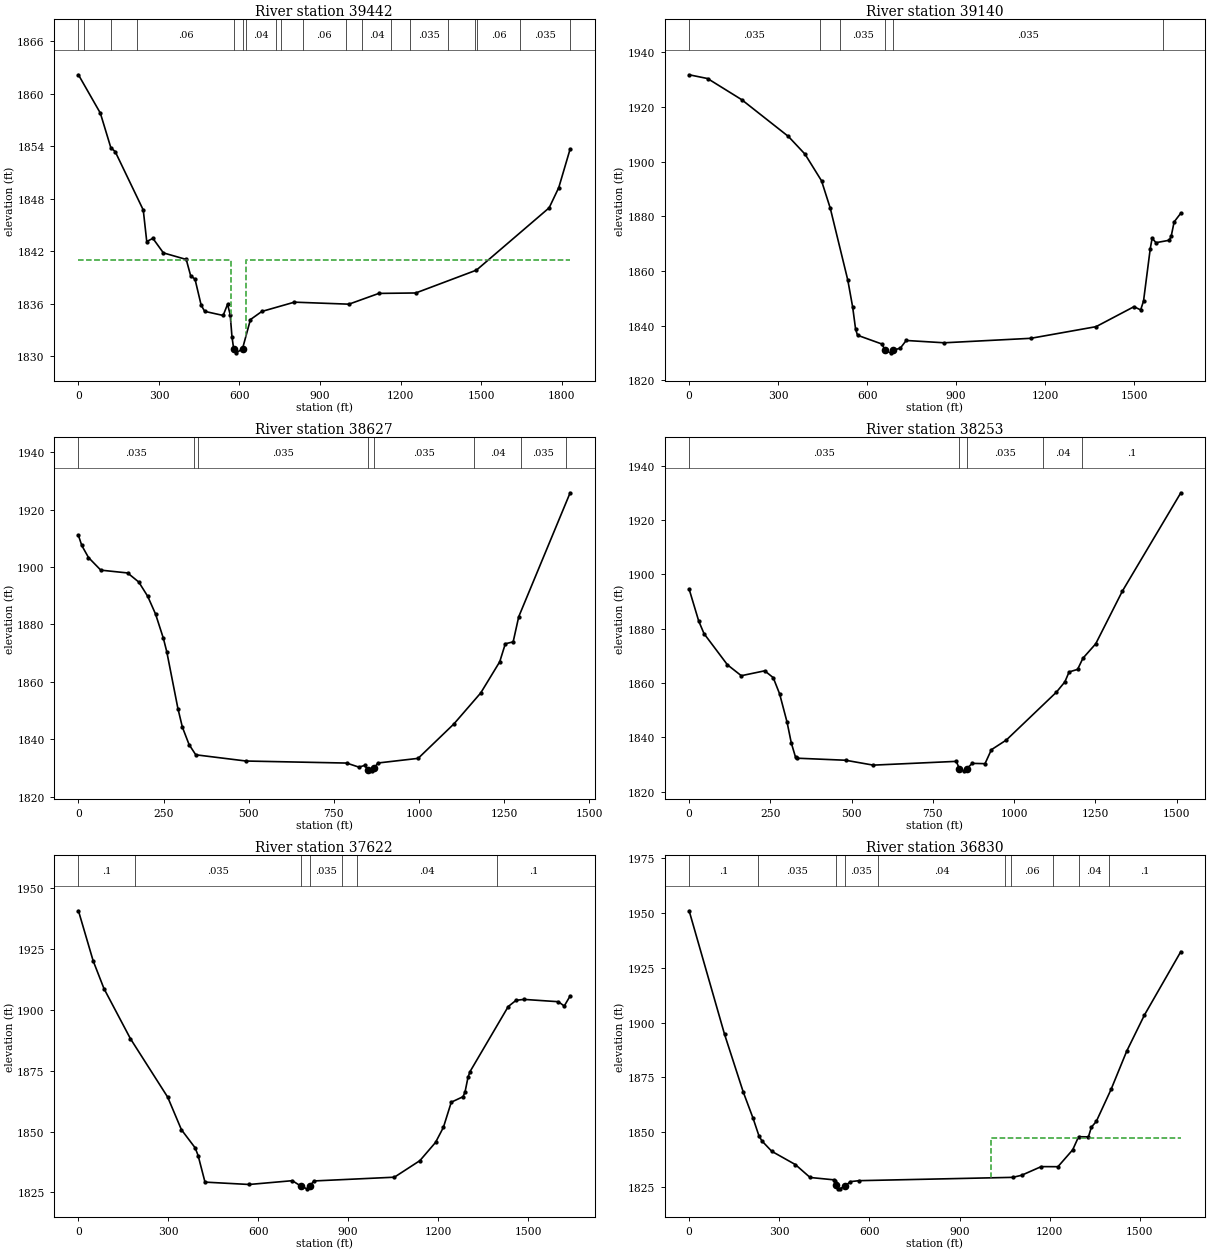
Type RM Length L Ch R = 1 ,39442   ,300.9,302,303.3
XS GIS Cut Line= 4
     2050576.322      156286.943     2050621.895      156629.825
     2051750.801      157139.373     2051757.312      157386.769
#Sta/Elev= 30
       0 1862.16    81.6 1857.78   120.7 1853.83     137 1853.38   241.5 1846.71
   254.5 1843.11   277.4 1843.47   316.5 1841.81   401.6 1841.06     418 1839.21
   434.4  1838.8   457.3 1835.83   470.4 1835.13   539.2 1834.66   555.6 1835.94
   565.4 1834.75     572 1832.24   578.5 1830.82   588.4 1830.39   611.3 1830.86
   640.8 1834.19   683.4 1835.12   804.6 1836.18  1007.8 1835.95  1119.2 1837.18
  1256.8 1837.23  1482.9 1839.84  1753.8 1846.96  1789.6 1849.27    1832 1853.68
#Mann= 19 ,-1 , 0
       0      .1       0      20     .06       0     120     .08       0
     220     .06       0   578.5    .045       0   611.3     .06       0
   625.9     .04       0   735.9     .06       0   755.9    .035       0
   835.9     .06       0   995.9    .035       0  1055.9     .04       0
  1165.9     .06       0  1235.9    .035       0  1375.9     .04       0
  1475.9    .035       0  1485.9     .06       0 1644.47    .035       0
 1831.95     .04       0
#XS Ineff= 2 , 0
             568    1841     623            1841
Permanent Ineff=
       F       F
Bank Sta=578.5,611.3
XS Rating Curve= 0 ,0
Exp/Cntr=0.5,0.3

Type RM Length L Ch R = 1 ,39140   ,502.1,513.2,507.6
XS GIS Cut Line= 3
     2050127.755      156689.597     2051451.322      157386.769
     2051438.301       157547.36
#Sta/Elev= 30
       0 1931.84    62.3 1930.46   177.2 1922.72   334.6 1909.25   390.4 1902.79
   446.2 1893.02   475.7 1882.96   534.7 1856.66   551.1 1846.81     561 1838.69
   567.5 1836.46   649.6 1833.25   660.9 1830.92   679.1 1830.02   685.6 1830.88
   711.9 1831.76   731.6 1834.55   859.5  1833.7  1151.5 1835.34  1371.3  1839.6
  1499.2 1846.92  1521.7 1845.74  1531.4 1848.99    1554 1868.13  1560.4 1872.02
  1573.3 1870.36  1618.4 1871.25  1624.8  1872.8  1634.5 1877.96  1657.1 1881.17
#Mann= 6 ,-1 , 0
       0    .035       0     440      .1       0     510    .035       0
   660.9    .045       0   685.6    .035       0 1595.95     .06       0
Bank Sta=660.9,685.6
XS Rating Curve= 0 ,0
Exp/Cntr=0.3,0.1

Type RM Length L Ch R = 1 ,38627   ,364.3,374.1,372.5
XS GIS Cut Line= 2
     2050040.388      156850.084     2051043.336      157888.071
#Sta/Elev= 30
       0    1911     9.8 1907.51    29.5 1903.32    65.6 1898.92   144.3 1897.94
   177.1 1894.78   203.4 1889.79   226.4 1883.61   249.3 1875.17   259.2 1870.55
     292  1850.7   305.1 1844.22   324.8 1838.13   344.4 1834.57   492.1  1832.4
   787.3 1831.69   823.4 1830.27   839.8 1830.86   849.6 1829.37   862.7 1828.98
   868.7 1830.05   879.1 1831.71   997.2 1833.33  1102.2 1845.33  1180.9 1856.12
  1236.7 1866.99  1253.1 1873.26  1276.1 1873.92  1292.5 1882.69  1443.4 1925.88
#Mann= 8 ,-1 , 0
       0    .035       0     340      .1       0     350    .035       0
   849.6    .045       0   868.7    .035       0    1160     .04       0
    1300    .035       0    1430      .1       0
Bank Sta=849.6,868.7
XS Rating Curve= 0 ,0
Exp/Cntr=0.3,0.1

Type RM Length L Ch R = 1 ,38253   ,624.5,631.2,622
XS GIS Cut Line= 3
     2049884.048      156998.748     2050622.329       158024.79
     2050814.603      158182.776
#Sta/Elev= 30
       0 1894.61    29.5 1882.86    45.8 1878.23   117.9 1866.75   160.5 1862.74
   232.5 1864.54   258.7 1862.03   278.4 1856.06   301.3 1845.65   314.4 1837.96
   327.5  1832.7   330.8 1832.38   481.4 1831.62   566.5 1829.82     822 1831.21
   831.8 1828.42   844.9 1827.72   853.8 1828.47   871.1 1830.47   910.4 1830.36
     930  1835.5   975.9 1839.05  1129.8 1856.65    1156 1860.45  1169.1 1864.12
  1195.3 1865.07  1211.6 1869.16    1251 1874.48  1332.8 1893.83  1512.9 1930.08
#Mann= 5 ,-1 , 0
       0    .035       0   831.8    .045       0   853.8    .035       0
    1090     .04       0    1210      .1       0
Bank Sta=831.8,853.8
XS Rating Curve= 0 ,0
Exp/Cntr=0.3,0.1

Type RM Length L Ch R = 1 ,37622   ,777.7,792,774.1
XS GIS Cut Line= 3
     2049432.659      157159.339     2050279.881       158020.45
     2050693.076      158148.922
#Sta/Elev= 30
       0 1940.67    49.1 1920.11    85.1 1908.73   173.5 1888.13   297.9  1864.1
   343.7 1850.73   389.6 1843.27   399.4  1840.1   422.3 1829.22   569.6 1828.25
   713.7 1829.81   743.1 1827.51   762.8 1826.46   772.6  1827.7   785.7  1829.7
  1054.2 1831.24  1139.3 1838.04  1191.6 1845.53  1217.8 1851.72  1244.1 1862.05
  1283.4 1864.31    1290 1866.27  1299.8 1872.21  1306.4 1874.56  1434.2 1901.35
  1460.4  1903.9  1486.6 1904.27  1601.4 1903.32    1621 1901.55  1640.7 1905.68
#Mann= 7 ,-1 , 0
       0      .1       0     190    .035       0   743.1    .045       0
   772.6    .035       0     880     .06       0     930     .04       0
 1398.01      .1       0
Bank Sta=743.1,772.6
XS Rating Curve= 0 ,0
Exp/Cntr=0.3,0.1

Type RM Length L Ch R = 1 ,36830   ,973.7,993.5,988.3
XS GIS Cut Line= 3
     2049148.805      157420.623      2050016.86      158288.679
     2050424.846      158319.061
#Sta/Elev= 30
       0 1951.01   117.8  1894.7     180 1868.39   212.8 1856.37   232.4 1848.34
   242.2 1846.04     275 1841.29   353.6 1835.23   402.7 1829.34   481.2 1828.28
   484.5 1827.52   487.8 1825.69   494.3  1824.2   500.9 1824.16   517.2 1825.23
   536.9 1827.45   566.3 1827.89    1077  1829.4  1106.5 1830.34    1172  1834.3
  1227.6 1834.26  1276.7 1841.95  1296.4 1847.93  1329.1 1847.87  1338.9 1852.27
  1355.3 1854.91  1404.4  1869.5  1456.7 1887.02  1515.6 1903.45  1636.7 1932.38
#Mann= 10 ,-1 , 0
       0      .1       0     230    .035       0   487.8    .045       0
   517.2    .035       0     630     .04       0    1050    .035       0
    1070     .06       0    1210    .035       0 1297.62     .04       0
 1397.62      .1       0
#XS Ineff= 2 , 0
                         1005.31         1847.33
Permanent Ineff=
       F       F
Bank Sta=487.8,517.2
XS Rating Curve= 0 ,0
Exp/Cntr=0.3,0.1

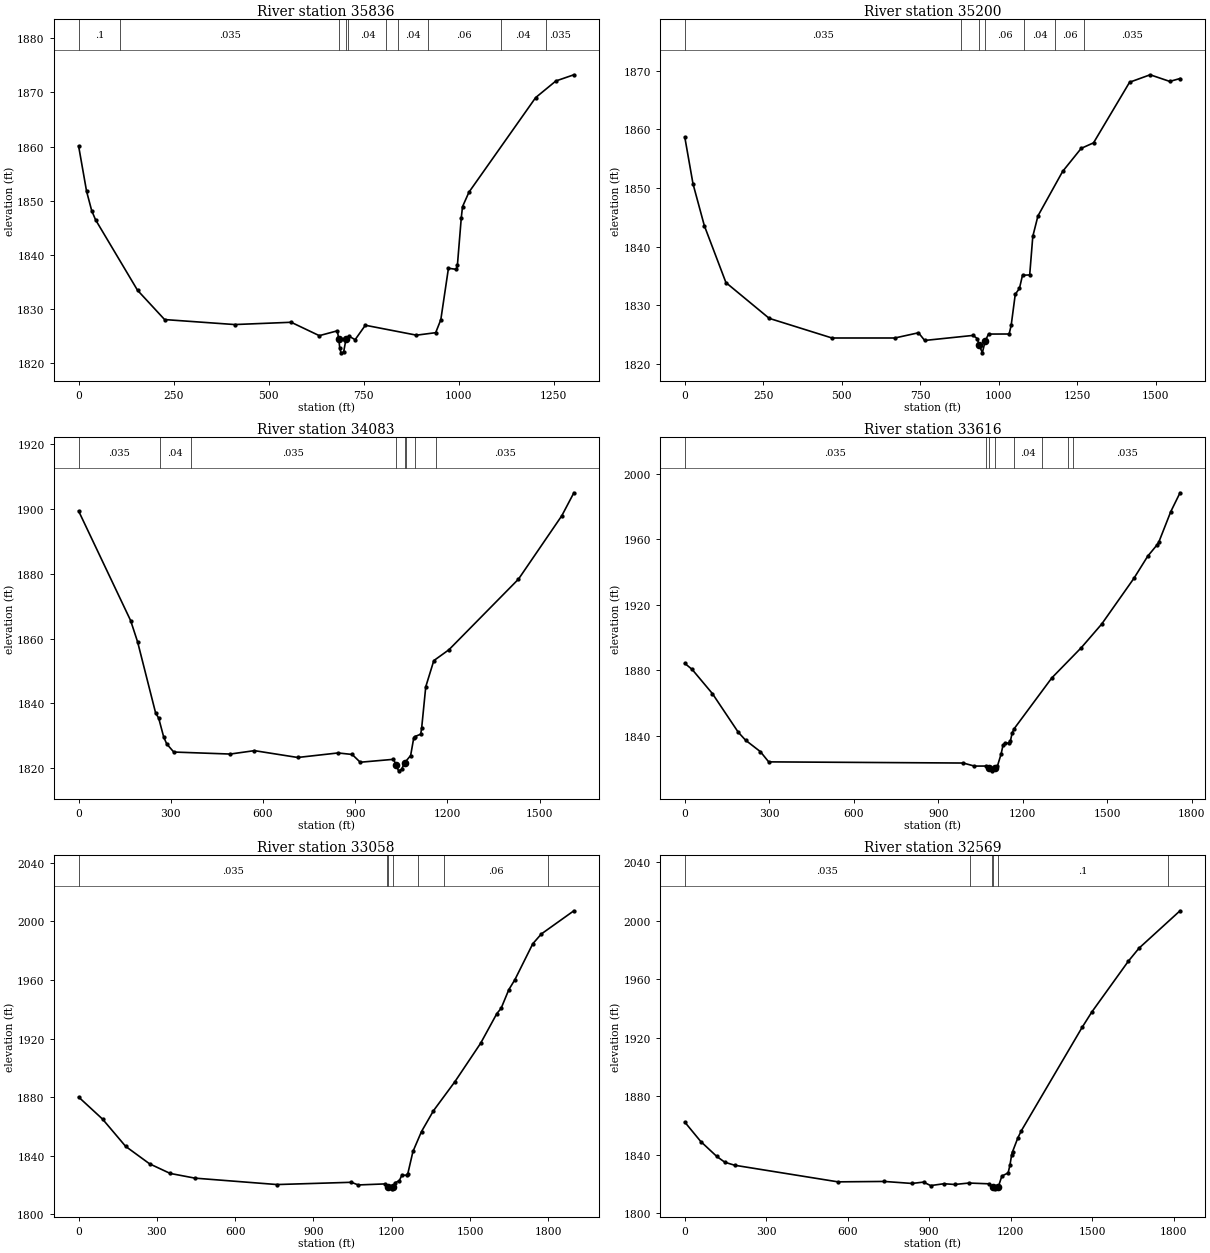
Type RM Length L Ch R = 1 ,35836   ,622.4,636.2,628.9
XS GIS Cut Line= 3
2049108.80978774157581.1926684632049340.31018997158595.498554544
2049552.71777553158750.627690062
#Sta/Elev= 30
       0 1860.12      21 1851.75    34.4  1848.2    44.5 1846.52   155.1  1833.5
   226.3  1828.1   410.7 1827.18   559.4  1827.6   633.4 1825.13   680.6 1826.02
   684.7 1824.57   687.3 1822.79   690.7 1821.96   697.4 1822.07   703.71824.506
   710.8 1825.06   727.7 1824.39   754.6 1827.05   889.2 1825.22   939.7 1825.68
   953.2 1828.07   973.3 1837.57   994.3 1837.36   996.9 1838.15    1007 1846.82
  1010.3 1848.93  1027.2  1851.6  1202.8 1869.06  1256.1 1872.13  1303.4 1873.27
#Mann= 10 ,-1 , 0
       0      .1       0     110    .035       0   684.7    .045       0
   703.7    .035       0     710     .04       0     810     .06       0
     840     .04       0     920     .06       0 1110.39     .04       0
 1230.39    .035       0
Bank Sta=684.7,703.7
XS Rating Curve= 0 ,0
Exp/Cntr(USF)=0,0
Exp/Cntr=0.3,0.1

Type RM Length L Ch R = 1 ,35200   ,1110.3,1117.4,1113
XS GIS Cut Line= 2
     2048967.291      157593.942     2048905.749      159169.755
#Sta/Elev= 30
       0 1858.67    26.2  1850.7    62.3 1843.56   131.1 1833.86   268.8 1827.77
   468.8 1824.42   668.8 1824.42   744.2 1825.31   763.9    1824     918 1824.86
   931.1 1824.33   937.7  1823.2   947.5 1821.89   956.7 1823.92   967.2 1825.09
  1032.8  1825.1  1039.3 1826.56  1052.4 1831.88  1065.6 1832.86  1075.4 1835.11
  1098.3 1835.17  1108.2 1841.75  1124.6 1845.23  1203.2 1852.81  1262.3 1856.74
  1301.6 1857.68  1416.4 1868.01  1481.9 1869.28  1544.2 1868.15    1577 1868.64
#Mann= 7 ,-1 , 0
       0    .035       0     880     .06       0   937.7    .045       0
   956.7     .06       0    1080     .04       0    1180     .06       0
    1270    .035       0
Bank Sta=937.7,956.7
XS Rating Curve= 0 ,0
Exp/Cntr=0.3,0.1

Type RM Length L Ch R = 1 ,34083   ,460.2,466.9,457.2
XS GIS Cut Line= 3
     2048588.909      157468.366     2048454.331      157660.069
     2048224.326      159017.846
#Sta/Elev= 30
       0 1899.42   169.2 1865.56   191.9 1858.97   250.6 1836.97   260.5  1835.4
   276.8 1829.56   286.7 1827.42   309.6 1824.92   493.2  1824.3     572 1825.35
   712.9 1823.24   844.1 1824.64     890 1824.17   916.2 1821.77  1024.4 1822.67
  1033.2  1820.9  1040.8 1819.11  1050.7 1819.55  1060.5 1821.59  1080.2 1823.84
    1090 1829.12  1093.3 1829.68    1113 1830.44  1116.2 1832.45  1129.4  1845.1
  1155.6 1853.18  1204.8 1856.54    1431 1878.36    1572 1897.96  1611.3 1905.06
#Mann= 8 ,-1 , 0
       0    .035       0  264.22     .04       0  364.22    .035       0
  1033.2    .045       0  1060.5    .035       0 1064.22     .04       0
 1094.22     .06       0 1164.22    .035       0
Bank Sta=1033.2,1060.5
XS Rating Curve= 0 ,0
Exp/Cntr=0.3,0.1

Type RM Length L Ch R = 1 ,33616   ,552.1,558,559.3
XS GIS Cut Line= 2
     2048371.895       157372.88     2047783.333      159030.324
#Sta/Elev= 30
       0 1884.35    26.2 1880.64    98.3 1865.86     190 1842.33   216.2 1837.44
   268.6 1830.49     298 1824.27   989.1 1823.56  1028.4  1821.7    1071 1821.73
  1080.8 1820.29  1090.7  1818.8  1100.5 1820.34  1110.3 1821.69  1123.4 1829.08
    1130  1834.3  1136.5 1835.66  1152.9 1835.76  1156.2 1836.84  1162.7 1841.93
  1169.3 1844.39  1303.6  1875.5  1408.4 1893.95  1480.4 1908.26  1595.1 1936.22
  1644.2 1949.74    1677 1956.55  1683.5 1958.32  1726.1 1976.94  1758.8 1988.37
#Mann= 8 ,-1 , 0
       0    .035       0    1070     .06       0  1080.8    .045       0
  1100.5     .06       0    1170     .04       0    1270    .035       0
    1360     .06       0    1380    .035       0
Bank Sta=1080.8,1100.5
XS Rating Curve= 0 ,0
Exp/Cntr=0.3,0.1

Type RM Length L Ch R = 1 ,33058   ,489.7,489,481.7
XS GIS Cut Line= 3
     2048211.305       157203.61     2047464.777      158293.019
     2047451.756      158870.276
#Sta/Elev= 30
       0 1880.09    91.8 1865.01   180.2  1846.4     272 1834.47   350.6 1827.93
   445.7  1824.7   760.3 1820.32  1045.4 1821.86  1071.6 1820.05  1173.2 1820.75
  1186.3 1818.55  1199.4 1817.39    1206 1818.92  1212.5  1821.5  1228.9 1822.96
  1238.7 1826.66  1258.4 1826.73  1261.7 1827.82  1281.3 1842.93  1314.1 1856.55
    1360 1870.76    1442 1890.56  1540.5 1916.78  1602.8 1937.09  1619.2 1940.71
  1648.7 1953.45  1671.7 1960.16  1740.6  1984.8  1773.4 1991.48    1898 2007.31
#Mann= 7 ,-1 , 0
       0    .035       0    1180     .06       0  1186.3    .045       0
    1206     .06       0    1300      .1       0 1400.65     .06       0
 1800.65      .1       0
Bank Sta=1186.3,1206
XS Rating Curve= 0 ,0
Exp/Cntr=0.3,0.1

Type RM Length L Ch R = 1 ,32569   ,841.3,844.4,838
XS GIS Cut Line= 2
     2047625.367      157003.957     2046980.187      158709.979
#Sta/Elev= 30
       0  1862.2      59 1848.88   118.1 1838.65   147.6 1834.71   183.7 1832.66
   564.2 1821.29   734.8 1821.57   836.5  1820.2   879.2 1821.12   905.4 1818.74
   954.6    1820     994  1819.5  1046.5 1820.48  1121.9 1819.94  1133.8 1817.89
  1141.6 1816.51  1151.4 1816.94  1154.7 1817.96  1167.8 1825.25  1190.8 1827.42
  1197.4 1832.62  1203.9 1839.91  1207.2 1841.98  1226.9  1851.5    1240 1856.44
  1463.1 1926.97  1499.2 1937.59  1633.7 1972.36    1673 1981.26  1823.9 2006.83
#Mann= 6 ,-1 , 0
       0    .035       0    1050     .06       0    1130     .04       0
  1133.8    .045       0  1154.7      .1       0    1780    .035       0
Bank Sta=1133.8,1154.7
XS Rating Curve= 0 ,0
Exp/Cntr=0.3,0.1

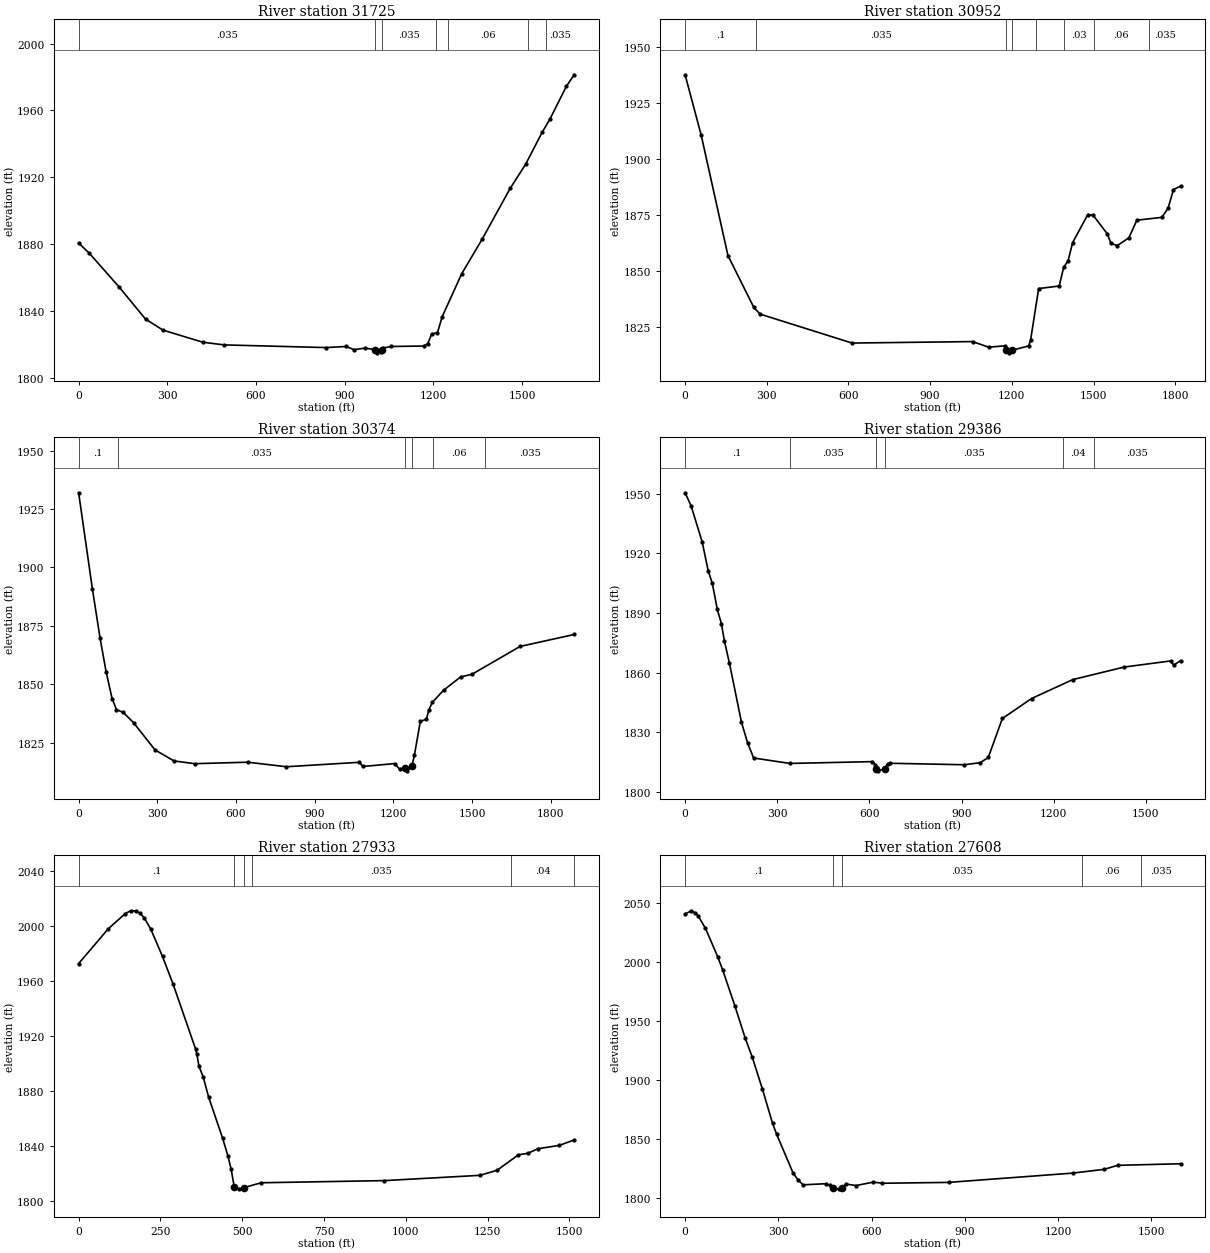
Type RM Length L Ch R = 1 ,31725   ,768.5,772.4,766.2
XS GIS Cut Line= 2
     2047213.041      156826.005     2046705.228      158423.228
#Sta/Elev= 30
       0 1880.73    36.1 1874.59   137.8 1854.23   226.3 1835.19   285.4  1828.6
   419.8 1821.38     492 1819.77   836.4 1818.17   905.2 1818.82   931.5 1816.91
   967.6 1817.83  1003.6 1816.95  1010.2 1815.02  1023.3 1815.69  1026.6 1816.92
  1029.9 1817.89  1056.1 1818.82  1167.6  1819.1  1180.8 1820.53  1193.9  1826.2
  1213.6 1827.14  1229.9 1836.75  1295.5 1862.31  1364.4  1882.9  1459.5 1913.38
    1512  1927.9  1567.8 1946.99    1594 1954.83  1649.8 1974.51    1676 1981.36
#Mann= 7 ,-1 , 0
       0    .035       0  1003.6    .045       0  1026.6    .035       0
    1210     .04       0    1250     .06       0    1520      .1       0
    1580    .035       0
Bank Sta=1003.6,1026.6
XS Rating Curve= 0 ,0
Exp/Cntr=0.3,0.1

Type RM Length L Ch R = 1 ,30952   ,576.6,577.8,574.9
XS GIS Cut Line= 3
     2046614.082      156548.228     2046162.694      158045.623
     2046227.798      158293.019
#Sta/Elev= 30
       0 1937.74      59 1910.77   157.4  1856.8   252.5 1833.56   275.4  1830.6
   613.1 1817.64  1055.8  1818.3  1114.8 1815.79  1173.8 1816.39  1180.3 1814.55
  1190.2 1813.26    1200 1814.39  1262.3 1816.38  1268.9 1819.08  1298.4 1842.04
  1373.8 1843.17  1390.2 1851.52  1406.6 1854.51    1423 1862.57  1478.7 1875.12
  1498.4 1874.84  1550.8  1866.5    1564 1862.26  1586.9 1861.25  1629.6 1864.74
  1659.1 1872.66  1750.9  1873.9  1773.8 1878.04  1793.5 1886.38  1819.8  1887.9
#Mann= 8 ,-1 , 0
       0      .1       0     260    .035       0  1180.3    .045       0
    1200    .035       0    1290     .06       0    1390     .03       0
    1500     .06       0 1703.95    .035       0
Bank Sta=1180.3,1200
XS Rating Curve= 0 ,0
Exp/Cntr=0.3,0.1

Type RM Length L Ch R = 1 ,30374   ,984.3,988.8,983.9
XS GIS Cut Line= 3
     2045958.701      156457.082     2045680.923      157880.693
     2045772.069       158310.38
#Sta/Elev= 30
       0 1931.99    52.4 1890.87    81.8 1869.71   104.8  1855.3   127.7 1843.81
   144.1 1839.15   170.3 1837.88   209.6 1833.49   291.4 1821.84   363.4 1817.12
     442 1815.95     645 1816.58   792.4 1814.64  1070.6 1816.54  1083.8 1814.74
  1204.9 1815.99  1224.5 1813.56  1244.2 1814.17    1254 1812.88  1270.4  1814.8
  1280.2 1819.48  1303.1 1834.05    1326 1835.01  1335.9 1839.15    1349 1842.24
  1391.5  1847.4    1457 1853.13  1499.6 1854.22  1683.2 1866.16  1889.7 1871.29
#Mann= 6 ,-1 , 0
       0      .1       0     150    .035       0  1244.2    .045       0
  1270.4     .04       0    1350     .06       0 1550.46    .035       0
Bank Sta=1244.2,1270.4
XS Rating Curve= 0 ,0
Exp/Cntr=0.3,0.1

Type RM Length L Ch R = 1 ,29386   ,1422.5,1452.1,1433
XS GIS Cut Line= 2
     2045333.701      156365.936     2045138.388      157967.498
#Sta/Elev= 30
       0 1950.52    19.7 1943.86    55.8 1925.67    75.4 1911.04    88.5 1904.99
   104.9 1891.78   118.1 1884.64   127.9 1875.95   144.3 1864.76   183.6 1834.91
   203.3  1824.7     223 1816.96     341 1814.22     610 1815.13   619.8 1813.59
   623.1 1811.66   629.5 1810.49   649.3 1811.56   659.1 1814.12   665.7 1814.31
   908.4 1813.56   960.8 1814.59   987.1 1817.22    1033 1836.86  1128.1 1846.91
  1262.5 1856.45  1429.8 1862.76  1580.6 1865.83  1590.5 1863.75  1613.4 1865.97
#Mann= 6 ,-1 , 0
       0      .1       0     340    .035       0   623.1    .045       0
   649.3    .035       0    1230     .04       0    1330    .035       0
Bank Sta=623.1,649.3
XS Rating Curve= 0 ,0
Exp/Cntr=0.3,0.1

Type RM Length L Ch R = 1 ,27933   ,325.5,325.4,323.5
XS GIS Cut Line= 3
     2044808.527      156313.853     2044673.978      156500.485
     2044574.152      157780.866
#Sta/Elev= 30
       0 1972.39    90.7 1997.73   142.6 2008.76   158.8 2010.81     175 2010.75
     188 2008.98   200.9  2005.5   220.4 1997.48   256.3 1977.59     289 1957.24
   357.8 1909.97   361.1 1906.76   367.7 1897.76   380.8 1889.89   397.2 1875.29
   439.8 1845.52   456.1 1832.57     466 1822.86   475.8 1809.57   488.9 1808.52
   505.3 1809.43   557.7 1812.94   934.5 1814.51    1226 1818.34  1278.5 1821.98
    1344 1833.28  1373.5 1834.39    1403 1837.69  1468.5 1840.11  1514.3 1844.07
#Mann= 6 ,-1 , 0
       0      .1       0   475.8    .045       0   505.3      .1       0
  530.08    .035       0 1320.08     .04       0 1514.34    .035       0
Bank Sta=475.8,505.3
XS Rating Curve= 0 ,0
Exp/Cntr=0.3,0.1

Type RM Length L Ch R = 1 ,27608   ,522.1,528.1,527.3
XS GIS Cut Line= 3
     2044496.027      156253.089     2044345.802      156565.859
     2044274.673      157811.248
#Sta/Elev= 30
       0 2040.42    19.6  2043.2    32.7 2041.47    42.6 2038.65    65.5 2028.31
   104.8 2004.33   121.1 1992.89   160.4 1962.41   193.1 1935.43     216 1919.16
   248.8 1891.99   281.5 1862.86   294.6 1853.68     347 1821.14   363.4 1814.94
   379.7 1810.85   451.8 1811.75   464.8 1810.46   474.7 1807.99   494.3 1807.43
   504.1 1807.99   517.2 1811.53     550 1810.23   605.6 1813.13   635.1 1812.17
   847.9 1812.89  1247.3 1820.77  1348.8 1823.98  1391.4 1827.36  1594.4  1828.7
#Mann= 5 ,-1 , 0
       0      .1       0   474.7    .045       0   504.1    .035       0
 1276.98     .06       0 1466.98    .035       0
Bank Sta=474.7,504.1
XS Rating Curve= 0 ,0
Exp/Cntr=0.3,0.1

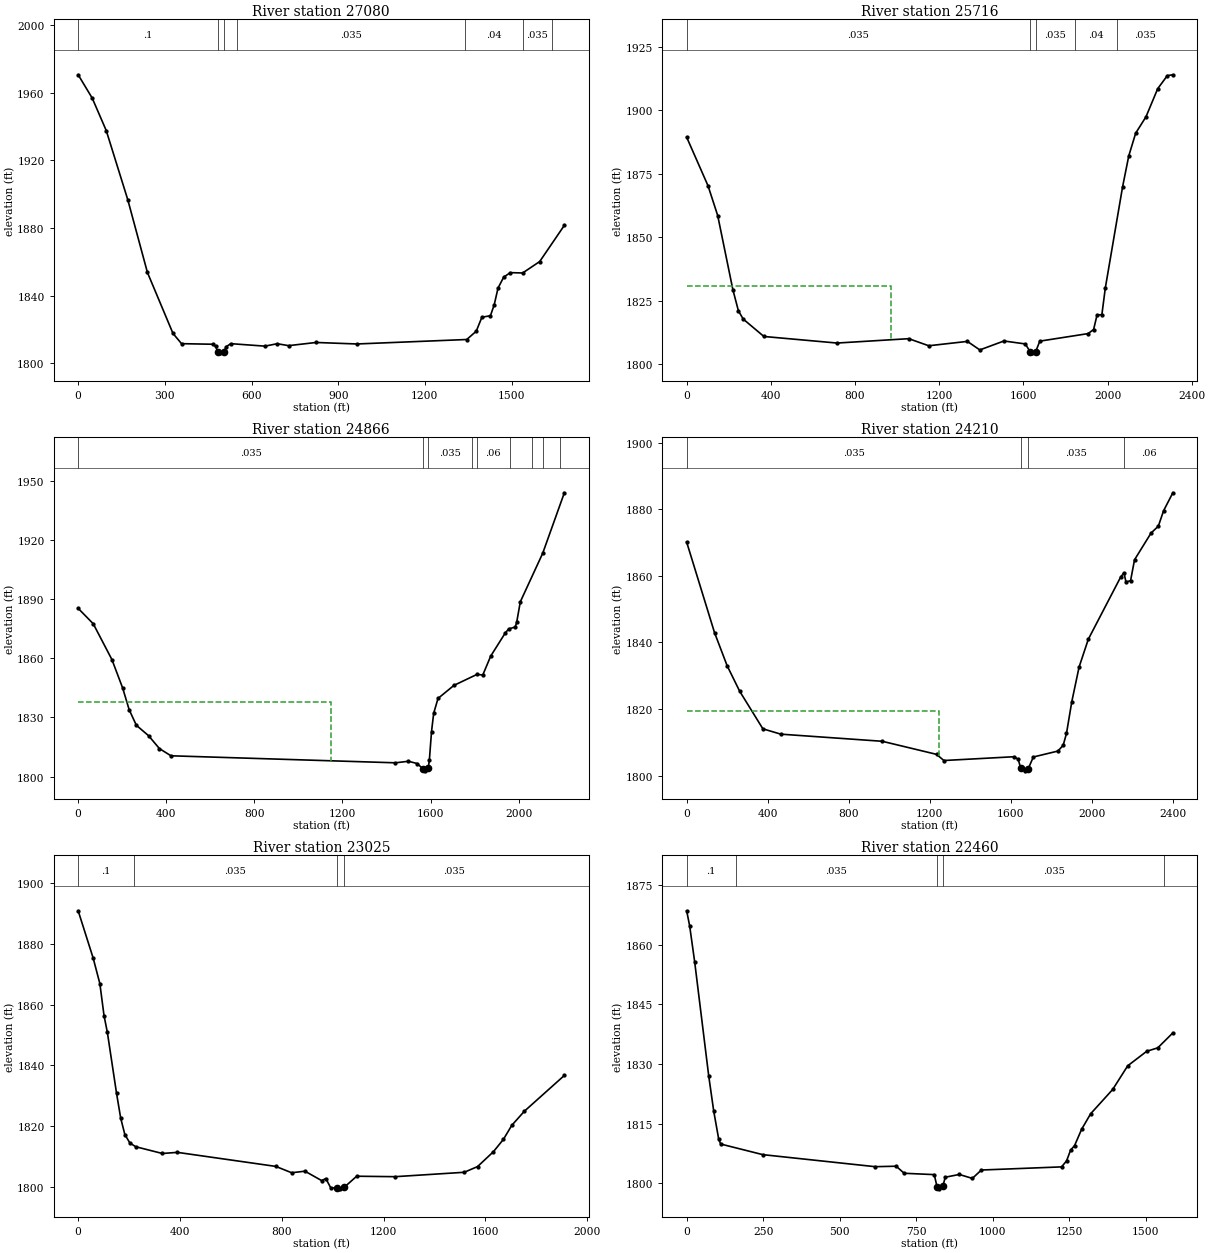
Type RM Length L Ch R = 1 ,27080   ,1351.2,1363.6,1346.3
XS GIS Cut Line= 3
     2044161.826      156040.415     2043983.874      156201.005
     2043775.541      157628.957
#Sta/Elev= 30
       0  1970.6    48.6 1956.82    97.2 1937.62   171.7 1896.76   239.7 1853.75
   328.2  1817.7   357.8 1811.65     466 1811.31   475.8 1810.11   483.1 1806.85
   492.2 1806.23   505.4 1806.81   511.9 1809.81   528.3 1811.65   646.4 1810.19
     689 1811.62   728.4 1810.48   823.5 1812.36   964.5 1811.47    1345 1814.11
  1377.8 1819.01  1397.4 1827.27    1427 1828.18  1440.1 1834.67  1453.2 1844.51
  1472.9 1850.98  1495.8 1853.64  1538.5 1853.44  1597.5  1860.2  1682.8 1881.59
#Mann= 7 ,-1 , 0
       0      .1       0   483.1    .045       0   505.4      .1       0
   549.7    .035       0  1339.7     .04       0  1539.7    .035       0
  1639.7      .1       0
Bank Sta=483.1,505.4
XS Rating Curve= 0 ,0
Exp/Cntr=0.3,0.1

Type RM Length L Ch R = 1 ,25716   ,836.8,850.1,858.3
XS GIS Cut Line= 4
     2043849.326      155406.735     2043393.596      155541.283
     2043202.624      157181.908     2043094.117      157329.478
#Sta/Elev= 30
       0 1889.44   101.6 1870.28   147.5 1858.56   219.6 1829.34   245.8 1821.03
   268.7 1817.76     367  1810.9   714.4 1808.31  1055.2 1810.03  1150.3 1807.24
  1333.8 1808.96  1392.8  1805.6  1507.5 1809.12  1609.1 1807.96    1632 1804.88
  1638.6 1804.45  1658.2 1804.87  1677.9 1809.06  1907.3 1812.03  1933.5 1813.64
  1949.9 1819.36  1972.8 1819.49  1989.2 1830.03  2071.2 1869.88  2100.7 1882.11
  2133.4 1891.02  2182.5  1897.5  2238.1 1908.56  2283.9 1913.71    2310 1914.04
#Mann= 5 ,-1 , 0
       0    .035       0    1632    .045       0  1658.2    .035       0
 1845.18     .04       0 2045.18    .035       0
#XS Ineff= 2 , 0
          969.47 1830.71
Permanent Ineff=
       F       F
Bank Sta=1632,1658.2
XS Rating Curve= 0 ,0
Exp/Cntr=0.3,0.1

Type RM Length L Ch R = 1 ,24866   ,648.1,656.6,631.7
XS GIS Cut Line= 3
     2043831.964      155311.248     2043493.423       155332.95
     2042234.742      156713.158
#Sta/Elev= 30
       0 1885.46    68.5 1877.62   153.3 1859.41   202.2 1844.91   231.6 1833.92
   264.2 1826.03   319.7 1820.73   368.7 1814.21   421.2 1810.53  1440.4 1806.96
  1499.3 1807.74  1538.7 1806.61  1564.9 1803.95  1574.7 1802.88 1589.22 1804.22
  1594.4 1808.32  1604.2 1822.86    1614 1832.14  1633.7 1839.68  1705.8  1846.3
  1810.7  1851.9  1836.9 1851.58  1872.9  1861.2  1938.5 1872.87  1954.8 1875.05
  1984.4 1875.96  1990.9 1878.44  2007.3  1888.8  2108.9 1913.44  2207.2  1944.2
#Mann= 9 ,-1 , 0
       0    .035       0  1564.9    .045       0 1589.22    .035       0
 1789.24     .04       0 1809.24     .06       0 1959.24     .04       0
 2059.24     .06       0 2109.24     .04       0 2189.24      .1       0
#XS Ineff= 2 , 0
         1148.03 1837.88
Permanent Ineff=
       F       F
Bank Sta=1564.9,1589.22
XS Rating Curve= 0 ,0
Exp/Cntr=0.3,0.1

Type RM Length L Ch R = 1 ,24210   ,1155.3,1184.2,1152.2
XS GIS Cut Line= 4
     2043797.242      155154.998     2043011.652      155150.658
     2042230.402      155988.332     2042087.173       156435.38
#Sta/Elev= 30
       0 1870.17   137.5 1842.98   199.7 1833.04   261.9 1825.34   376.4 1814.06
   464.8 1812.46   965.6 1810.32    1234 1806.39    1270 1804.54  1616.9 1805.68
  1636.5 1804.92  1649.6 1802.28  1669.2 1801.44  1685.6 1801.97  1711.8  1805.6
  1832.9 1807.38    1859 1809.11  1875.4 1812.68  1901.6 1822.23  1937.6 1832.62
  1983.2 1840.99    2143 1859.67  2159.2 1860.95    2169 1858.18  2191.8 1858.58
  2211.4 1864.86  2292.9 1872.88  2328.8 1874.94  2354.8 1879.58  2400.5 1884.98
#Mann= 4 ,-1 , 0
       0    .035       0  1649.6    .045       0  1685.6    .035       0
 2161.05     .06       0
#XS Ineff= 2 , 0
         1246.47  1819.4
Permanent Ineff=
       F       F
Bank Sta=1649.6,1685.6
XS Rating Curve= 0 ,0
Exp/Cntr=0.3,0.1

Type RM Length L Ch R = 1 ,23025   ,563.4,565.7,557.2
XS GIS Cut Line= 3
     2042438.735      154148.054     2041683.527      155597.707
     2041464.923      155765.081
#Sta/Elev= 30
       0 1890.99      59 1875.37    85.2 1866.98   101.6 1856.41   114.6 1850.94
   150.7 1830.82   167.1 1822.59   183.4 1817.19   203.1 1814.41     226 1813.17
   330.8 1810.94   389.8 1811.31   776.3 1806.68   838.6 1804.59     891  1805.1
   956.5    1802   972.9 1802.67   992.5 1799.57  1015.5 1799.58  1028.6 1799.28
    1045 1799.78  1094.1 1803.44  1244.8 1803.29  1516.6 1804.74  1569.1 1806.63
  1631.3 1811.53  1670.6 1815.61  1703.4 1820.22  1752.6 1824.86  1909.9 1836.68
#Mann= 4 ,-1 , 0
       0      .1       0     220    .035       0  1015.5    .045       0
    1045    .035       0
Bank Sta=1015.5,1045
XS Rating Curve= 0 ,0
Exp/Cntr=0.3,0.1

Type RM Length L Ch R = 1 ,22460   ,689,693.8,681.6
XS GIS Cut Line= 2
     2041813.569      154286.945     2041184.395      155745.276
#Sta/Elev= 30
       0 1868.59     9.8 1864.79    26.2 1855.72      72 1827.04    88.4 1818.14
   104.8 1811.03   111.3 1809.84   248.9 1807.17   615.7 1804.14   684.4 1804.26
   710.6 1802.48   808.9 1802.14     818 1799.07   825.2 1798.56   836.9 1799.23
   844.9 1801.49   890.7 1802.18   933.3 1801.19   962.8  1803.3  1224.8 1804.09
  1241.1  1805.6  1254.2 1808.29  1267.3 1809.46  1290.3 1813.56  1319.7 1817.46
  1391.8 1823.59  1440.9 1829.55  1503.1 1833.21  1539.1 1834.07  1588.3 1837.83
#Mann= 5 ,-1 , 0
       0      .1       0     160    .035       0     818    .045       0
   836.9    .035       0    1560     .04       0
Bank Sta=818,836.9
XS Rating Curve= 0 ,0
Exp/Cntr=0.3,0.1