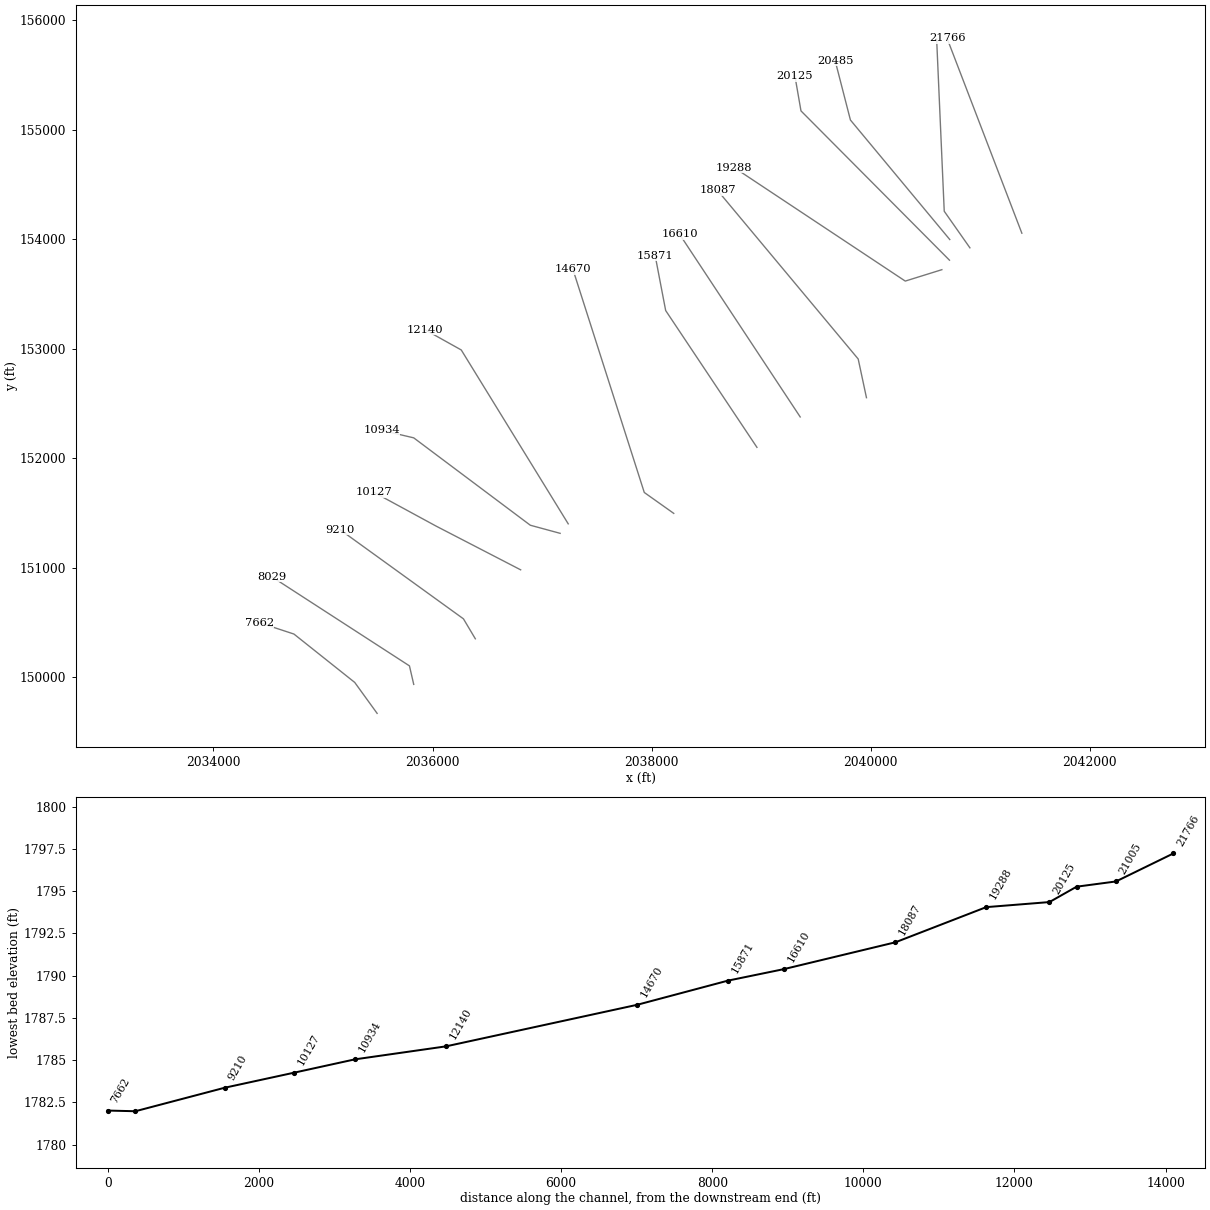
HEC-RAS study RICHCK_A.prj: RICHCK_A

--- RICHCK_A.g01 (geometry) --- (continued)

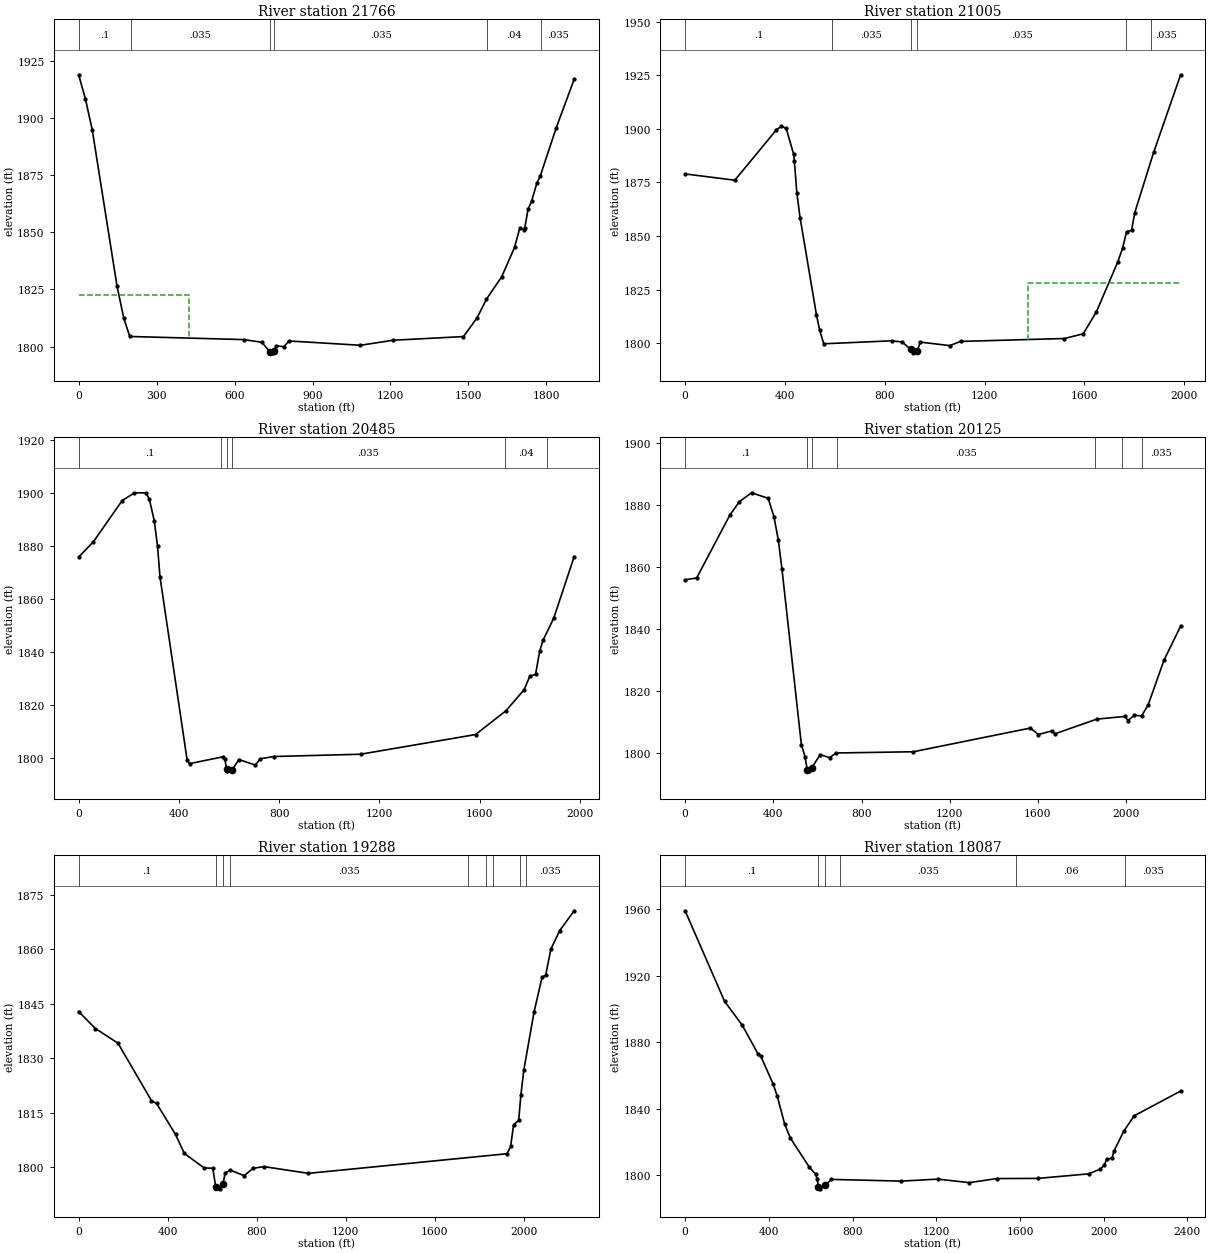
Type RM Length L Ch R = 1 ,21766   ,757.4,760.5,745.3
XS GIS Cut Line= 2
     2041380.902      154055.963     2040698.284      155836.422
#Sta/Elev= 30
       0 1918.87    26.2 1908.29    52.4 1894.78   147.4 1826.65   173.6 1812.44
   196.6 1804.39   635.6 1803.02   704.4 1801.86   736.5 1797.67     747 1797.23
   753.6 1798.04   760.1 1800.32   789.6  1799.9   809.3 1802.42  1084.5 1800.54
    1209 1802.73  1480.9 1804.35  1533.3 1812.57  1569.4 1820.74  1628.3 1830.59
  1677.5  1843.4  1697.1 1851.64  1713.5 1851.11  1716.8 1852.01  1729.9 1860.28
    1743 1863.52  1762.7 1871.32  1775.8 1874.43    1838 1895.74  1906.8  1916.9
#Mann= 6 ,-1 , 0
       0      .1       0     200    .035       0   736.5    .045       0
   753.6    .035       0    1570     .04       0    1780    .035       0
#XS Ineff= 2 , 0
          423.97  1822.5
Permanent Ineff=
       F       F
Bank Sta=736.5,753.6
XS Rating Curve= 0 ,0
Exp/Cntr=0.3,0.1

Type RM Length L Ch R = 1 ,21005   ,506.5,520.8,527.7
XS GIS Cut Line= 3
     2040906.617       153922.36     2040672.242      154256.561
     2040602.798      155832.082
#Sta/Elev= 30
       0 1878.98   199.2 1876.05   365.7 1899.52   385.3 1901.17   404.9 1900.24
   434.4 1888.32   437.7 1885.03   447.5 1870.27   460.6  1858.6   526.2  1813.3
   539.3 1806.01   555.7 1799.79   827.9 1801.18   870.5 1800.62   903.3 1797.13
   913.1 1795.57   929.5 1796.46   942.6 1800.56  1060.6 1798.94  1103.3 1800.89
  1519.7 1802.25  1595.1 1804.45  1647.5 1814.65  1732.8 1837.78  1752.5 1844.33
  1768.8 1852.06  1788.5 1852.65  1801.6 1860.99    1877 1889.01  1985.2  1925.2
#Mann= 6 ,-1 , 0
       0      .1       0  588.19    .035       0   903.3    .045       0
   929.5    .035       0 1768.19     .04       0 1868.19    .035       0
#XS Ineff= 2 , 0
                         1372.53            1828
Permanent Ineff=
       F       F
Bank Sta=903.3,929.5
XS Rating Curve= 0 ,0
Exp/Cntr=0.3,0.1

Type RM Length L Ch R = 1 ,20485   ,349.2,359.7,353.8
XS GIS Cut Line= 3
     2040722.806      153998.097     2039815.688      155090.111
       2039676.8      155630.042
#Sta/Elev= 30
       0  1875.8      59  1881.6   173.8 1897.09   222.9 1900.03   268.8 1899.98
     282 1897.65   301.6 1889.57   314.8 1879.88   324.6 1868.34   432.8 1799.38
   442.6 1797.98     577 1800.56   583.6 1799.63   590.2 1795.95   593.4 1795.26
   613.1 1795.67   639.3 1799.53   704.9 1797.42   724.6 1799.82   780.3 1800.66
  1124.6 1801.52  1583.6 1808.93    1705  1817.9  1777.1 1825.77    1800 1830.88
    1823 1831.61  1839.4 1840.26  1852.5  1844.4  1895.2 1852.69  1977.1 1875.95
#Mann= 6 ,-1 , 0
       0      .1       0     570    .035       0   590.2    .045       0
   613.1    .035       0 1699.63     .04       0 1869.63    .035       0
Bank Sta=590.2,613.1
XS Rating Curve= 0 ,0
Exp/Cntr=0.3,0.1

Type RM Length L Ch R = 1 ,20125   ,824.2,836.6,813.9
XS GIS Cut Line= 3
     2040719.985      153809.512       2039364.3      155173.445
     2039308.744      155492.889
#Sta/Elev= 30
       0 1855.89    52.4  1856.5   203.1 1876.76   245.7 1881.04   301.4 1883.94
   376.8 1882.16     403 1876.22   422.6 1868.77     439 1859.54   527.4 1802.72
   543.8 1798.93   553.7 1794.78   560.2 1794.35   573.3 1795.15   612.6 1799.59
   655.2 1798.58   684.7  1800.1  1035.2  1800.5    1566 1808.14    1602 1806.05
  1664.3 1807.24  1677.4 1806.29  1867.4 1811.02  1995.1 1811.88  2008.2 1810.55
  2037.7 1812.27  2070.4 1812.03  2099.9 1815.58    2172 1830.03  2247.3 1840.99
#Mann= 7 ,-1 , 0
       0      .1       0   553.7    .045       0   573.3      .1       0
     690    .035       0    1860     .04       0 1983.07     .06       0
 2073.07    .035       0
Bank Sta=553.7,573.3
XS Rating Curve= 0 ,0
Exp/Cntr=0.3,0.1

Type RM Length L Ch R = 1 ,19288   ,1189.5,1201,1174
XS GIS Cut Line= 3
     2040650.541      153722.707     2040316.339       153618.54
     2038753.839      154655.866
#Sta/Elev= 30
       0 1842.89    75.2 1838.22   176.7 1834.18   327.2 1818.34   350.1 1817.58
   435.3 1809.02   474.6 1803.82   563.2 1799.82   602.5 1799.72   615.6 1794.69
   635.3 1794.05   648.4 1795.49   658.3 1798.45   681.2  1799.2   743.5 1797.67
   782.9 1799.69     832 1800.17    1032 1798.32  1923.9 1803.72  1940.3 1805.72
  1953.4 1811.69  1976.4 1812.89  1986.2 1819.88  1999.3 1826.71  2045.2 1842.69
  2081.3 1852.35  2097.7 1852.89  2120.6 1860.01    2160 1865.14  2225.6 1870.65
#Mann= 9 ,-1 , 0
       0      .1       0   615.6    .045       0   648.4      .1       0
  680.06    .035       0 1750.06     .06       0 1830.06    .035       0
 1860.06     .06       0 1980.06     .04       0 2010.06    .035       0
Bank Sta=615.6,648.4
XS Rating Curve= 0 ,0
Exp/Cntr=0.3,0.1

Type RM Length L Ch R = 1 ,18087   ,1467,1477.6,1435.6
XS GIS Cut Line= 3
     2039962.117      152553.189     2039886.652      152906.735
      2038601.93      154447.533
#Sta/Elev= 30
       0 1959.14   188.9 1904.65   273.6 1890.25   348.5 1873.03   361.5 1871.73
   420.5 1855.05   440.2 1847.72   476.2 1830.69   502.5 1822.58   594.2 1804.88
   623.8 1800.75   630.3 1798.15   636.9 1793.37   646.7 1791.97   669.6 1794.16
   699.1 1797.64  1033.5 1796.62  1207.2 1797.81    1358 1795.69  1489.1 1798.15
  1685.8 1798.24  1928.4 1800.99  1984.1 1803.87  2003.8 1806.54  2013.6 1809.66
  2039.8  1810.5  2049.7  1814.9  2095.6 1826.52  2144.7 1835.81  2367.6 1850.78
#Mann= 6 ,-1 , 0
       0      .1       0   636.9    .045       0   669.6      .1       0
  741.51    .035       0 1581.51     .06       0 2101.51    .035       0
Bank Sta=636.9,669.6
XS Rating Curve= 0 ,0
Exp/Cntr=0.3,0.1

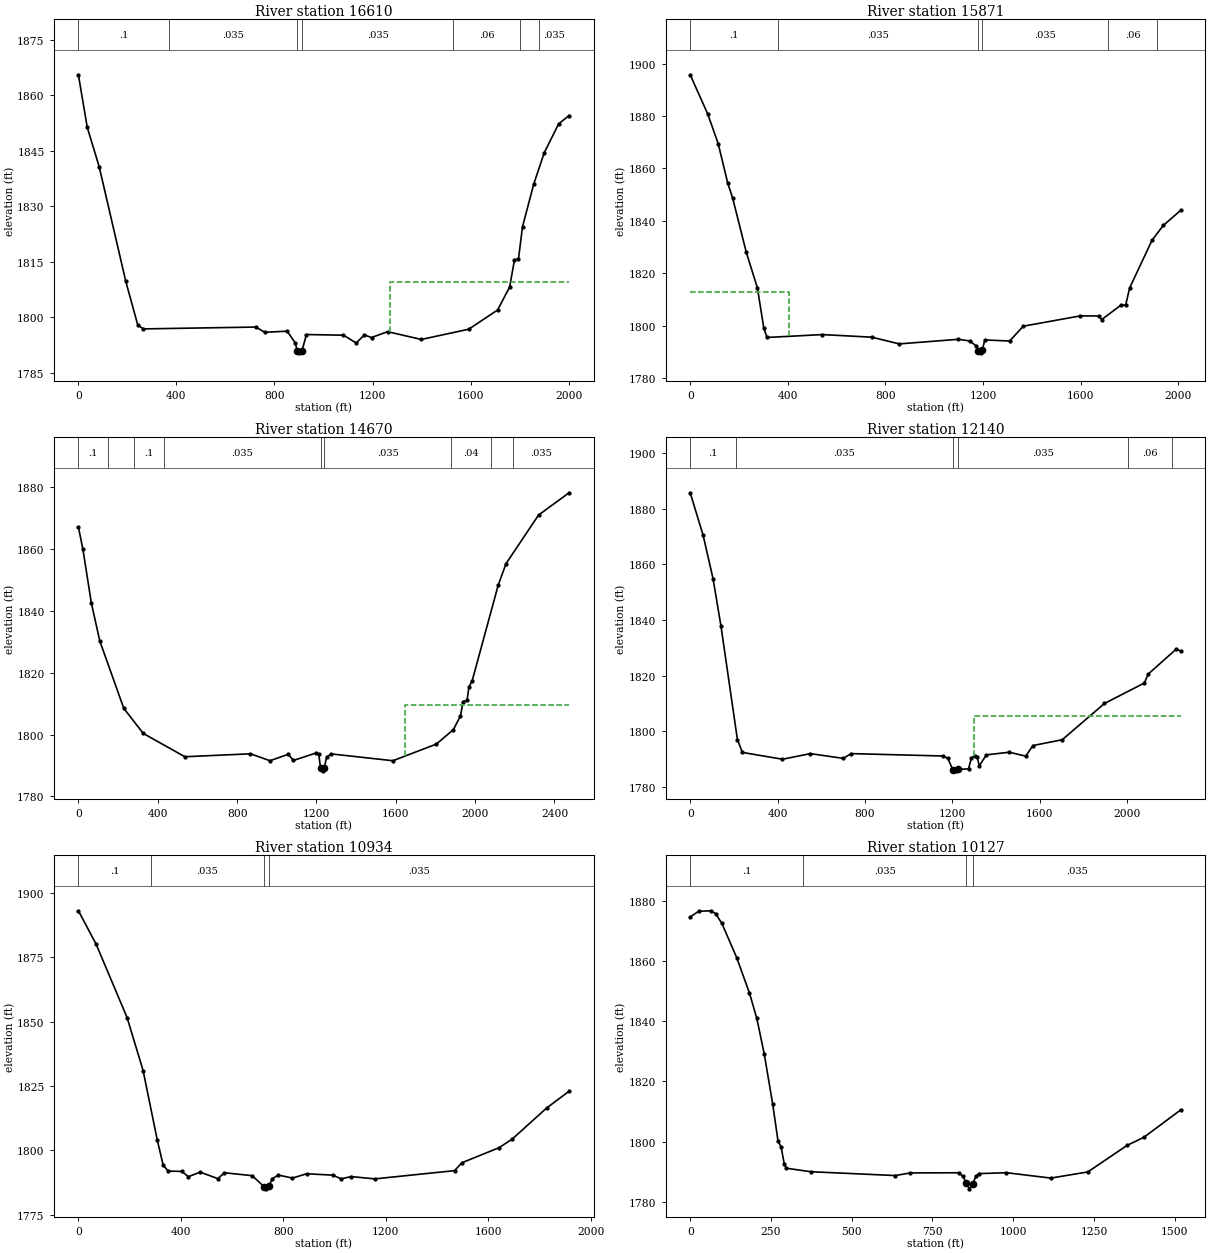
Type RM Length L Ch R = 1 ,16610   ,736.3,739,733.6
XS GIS Cut Line= 2
     2039357.138      152377.221     2038254.707      154048.228
#Sta/Elev= 30
       0 1865.54      36 1851.38    85.2 1840.59   193.3 1809.71   242.5 1797.84
   265.4 1796.85   724.1 1797.35   760.1 1795.94   851.9 1796.23   884.6 1793.07
   893.4 1790.93     901 1790.38   912.5 1791.01   930.5 1795.33  1081.2 1795.15
  1133.6 1793.05  1166.4 1795.22  1195.9 1794.52  1261.4  1796.1    1399    1794
  1592.4 1796.76  1710.3 1801.96  1759.4 1808.17  1779.1  1815.5  1795.5 1815.78
  1811.9 1824.46  1857.7 1835.98  1900.3 1844.42  1959.3 1852.27  2001.9 1854.52
#Mann= 7 ,-1 , 0
       0      .1       0     370    .035       0   893.4    .045       0
   912.5    .035       0    1530     .06       0    1800     .04       0
    1880    .035       0
#XS Ineff= 2 , 0
                         1273.24         1809.65
Permanent Ineff=
       F       F
Bank Sta=893.4,912.5
XS Rating Curve= 0 ,0
Exp/Cntr=0.3,0.1

Type RM Length L Ch R = 1 ,15871   ,1197.5,1201,1189.1
XS GIS Cut Line= 3
     2038962.173      152099.443     2038128.839      153349.443
     2038033.353      153848.575
#Sta/Elev= 30
       0 1895.71    72.2 1880.68   114.8 1869.43   154.2 1854.28   173.8 1848.78
   229.6 1828.13   275.5 1814.42   301.8 1799.02   314.9 1795.56   541.2 1796.66
   744.6 1795.67   856.1 1793.11  1098.8 1794.86  1144.8 1794.24    1171 1792.41
  1180.4 1790.37  1190.7  1789.7  1197.3 1790.84  1207.1 1794.62  1308.8  1794.2
  1364.6 1799.85  1597.4 1803.77  1676.1 1803.77  1685.9 1802.36  1764.6 1807.87
  1784.3 1807.93  1800.7 1814.49  1892.5 1832.66  1938.4 1838.26  2010.5  1844.1
#Mann= 6 ,-1 , 0
       0      .1       0     360    .035       0  1180.4    .045       0
  1197.3    .035       0 1712.31     .06       0 1912.31    .035       0
#XS Ineff= 2 , 0
          404.23 1813.02
Permanent Ineff=
       F       F
Bank Sta=1180.4,1197.3
XS Rating Curve= 0 ,0
Exp/Cntr=0.3,0.1

Type RM Length L Ch R = 1 ,14670   ,2502.3,2530.2,2515.8
XS GIS Cut Line= 3
     2038202.624      151496.144     2037933.527      151687.116
     2037280.966         153729.
#Sta/Elev= 30
       0 1867.13    22.9 1859.86    65.3 1842.58   107.8 1830.28   228.7  1808.5
   326.7 1800.38   536.5 1792.83   867.5 1793.78   965.8 1791.54  1057.6 1793.61
  1083.8 1791.63  1195.3 1793.97  1211.7 1793.65 1220.82  1789.1  1231.4 1788.27
    1239 1789.07    1251 1792.66    1274 1793.75  1585.3 1791.54    1805 1796.93
  1890.2  1801.6  1926.2 1806.05  1939.3 1810.65    1959 1811.04  1968.8 1815.38
  1985.2 1817.42  2116.3  1848.3  2155.7 1855.27  2319.6 1870.99  2473.6 1878.19
#Mann= 9 ,-1 , 0
       0      .1       0     150    .035       0     280      .1       0
  429.97    .035       0 1220.82    .045       0    1239    .035       0
 1879.97     .04       0 2079.97      .1       0 2189.97    .035       0
#XS Ineff= 2 , 0
                         1646.41         1809.64
Permanent Ineff=
       F       F
Bank Sta=1220.82,1239
XS Rating Curve= 0 ,0
Exp/Cntr=0.3,0.1

Type RM Length L Ch R = 1 ,12140   ,1187.8,1206,1202.4
XS GIS Cut Line= 3
     2037239.082      151400.658      2036262.52        152989.2
     2035928.319      153175.832
#Sta/Elev= 30
       0 1885.69      59 1870.49   104.9 1854.77   140.9 1837.85   216.3 1797.03
   239.2 1792.42   422.8 1789.98   550.6 1791.99   701.3 1790.28   737.4    1792
  1156.8 1791.14  1179.8 1790.35  1202.7  1786.2  1215.8 1785.81  1226.7 1786.31
  1274.8 1786.54  1287.9 1790.38  1304.3 1791.28  1314.1  1790.8    1324 1787.65
  1356.8 1791.55  1461.6  1792.5    1537 1791.08  1569.8  1794.9  1704.1 1796.98
  1897.4 1810.01  2080.6 1817.37    2097  1820.5  2224.6 1829.42  2247.5  1828.9
#Mann= 6 ,-1 , 0
       0      .1       0     210    .035       0  1202.7    .045       0
  1226.7    .035       0 2004.71     .06       0 2204.71    .035       0
#XS Ineff= 2 , 0
                         1301.41         1805.33
Permanent Ineff=
       F       F
Bank Sta=1202.7,1226.7
XS Rating Curve= 0 ,0
Exp/Cntr=0.3,0.1

Type RM Length L Ch R = 1 ,10934   ,794.4,806.1,800.8
XS GIS Cut Line= 4
     2037165.298      151313.853     2036893.076      151387.811
     2035828.492      152186.248     2035533.353      152255.693
#Sta/Elev= 30
       0 1893.11    68.9 1880.21   190.2 1851.59   252.6 1831.03   308.3 1803.89
   331.2  1794.2   350.9 1791.94   403.4 1791.81   429.6 1789.77   475.5 1791.54
   544.3 1789.01   570.5 1791.28   678.7 1790.16   724.3 1785.94   731.1 1785.04
   744.2 1786.26   757.4 1788.96   780.3  1790.4     836 1789.23   891.7 1790.91
   993.3 1790.35  1026.1 1788.92  1065.4 1789.81  1157.2 1788.91  1468.6 1792.11
  1498.1  1795.2  1642.2 1801.02  1694.3  1804.4    1828 1816.43    1916 1822.97
#Mann= 4 ,-1 , 0
       0      .1       0  282.09    .035       0   724.3    .045       0
   744.2    .035       0
Bank Sta=724.3,744.2
XS Rating Curve= 0 ,0
Exp/Cntr=0.3,0.1

Type RM Length L Ch R = 1 ,10127   ,901.8,917.2,895.3
XS GIS Cut Line= 3
     2036804.744      150980.449     2036034.061       151379.27
     2035461.874      151690.186
#Sta/Elev= 30
       0 1874.75    26.2 1876.66    65.5 1876.82    78.6 1875.86    98.2 1872.61
   144.1 1861.18   183.4 1849.46   206.3 1840.98   229.2 1829.19   255.4 1812.45
   271.8 1800.24   281.6 1798.08   291.4 1792.46     298 1791.11   373.3 1789.95
   635.3 1788.67   681.1 1789.55   831.7  1789.6   844.8 1788.36   854.7 1786.16
   864.5 1784.25   875.3    1786   884.1 1788.42   893.9 1789.32     979 1789.62
  1116.5 1787.83    1231 1789.88  1352.1 1798.69  1404.4  1801.4    1519 1810.57
#Mann= 4 ,-1 , 0
       0      .1       0     350    .035       0   854.7    .045       0
   875.3    .035       0
Bank Sta=854.7,875.3
XS Rating Curve= 0 ,0
Exp/Cntr=0.3,0.1

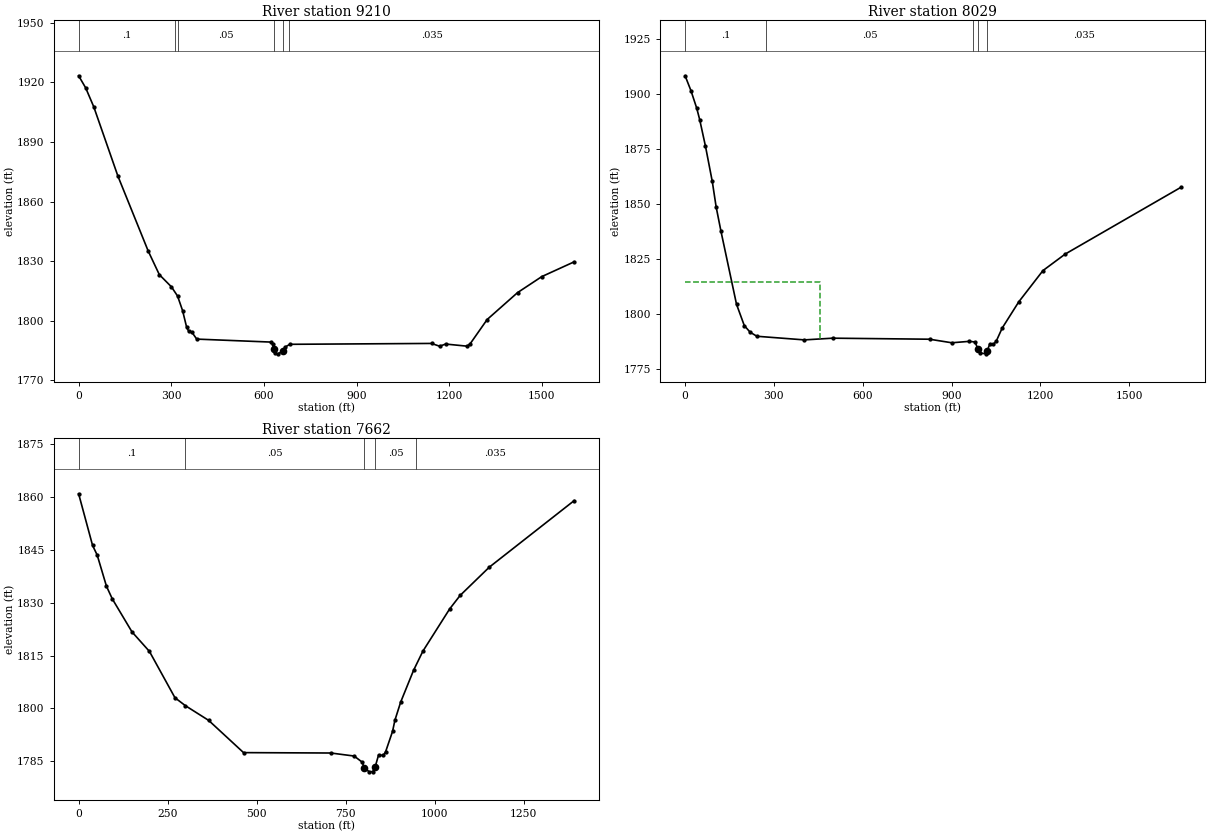
Type RM Length L Ch R = 1 ,9210    ,1163.6,1180.9,1170
XS GIS Cut Line= 3
     2036390.992      150350.311     2036282.485      150532.603
     2035154.013      151348.575
#Sta/Elev= 30
       0 1923.38    22.8 1917.29      49 1907.75   127.3 1872.81   225.2 1835.16
   261.3 1823.24   300.6 1817.09   320.3 1812.48   336.6 1805.14   349.8 1796.73
   356.3 1794.78   366.1 1794.38   382.5 1790.78   621.7 1789.29   628.3 1788.24
   631.6 1785.58   634.8 1783.68   644.7 1783.36     661 1784.66   667.6 1786.69
     684 1788.16  1142.7  1788.6  1168.9  1787.2  1188.6 1788.29  1257.4 1787.23
  1267.2 1788.27  1322.9 1800.64  1421.2 1814.17  1499.9 1822.26  1604.7 1829.69
#Mann= 6 ,-1 , 0
       0      .1       0  312.14     .12       0  322.14     .05       0
   631.6    .045       0     661     .05       0  682.14    .035       0
Bank Sta=631.6,661
XS Rating Curve= 0 ,0
Exp/Cntr=0.3,0.1

Type RM Length L Ch R = 1 ,8029    ,367.2,367.2,360.5
XS GIS Cut Line= 3
     2035828.492      149933.644      2035789.43      150102.915
      2034530.54      150918.519
#Sta/Elev= 30
       0  1908.4    19.7 1901.67    39.3 1893.65    49.2 1888.51    68.8 1876.38
    91.8 1860.35   104.9 1848.74   121.3 1837.61   173.7 1804.49   199.9 1794.83
   219.6 1791.81   242.5 1789.96     403 1788.31     498 1789.09   825.5 1788.62
   900.8    1787   959.8 1787.65   979.4 1787.36   989.2 1784.08   995.8 1782.39
  1015.4 1781.97  1020.1 1783.21  1028.5 1786.26  1041.6 1786.24  1051.4 1787.88
  1071.1 1793.71  1126.8 1805.58  1208.7 1819.83    1284 1827.35  1673.7 1857.61
#Mann= 5 ,-1 , 0
       0      .1       0  273.72     .05       0  973.72    .035       0
   989.2    .045       0  1020.1    .035       0
#XS Ineff= 2 , 0
          455.32 1814.47
Permanent Ineff=
       F       F
Bank Sta=989.2,1020.1
XS Rating Curve= 0 ,0
Exp/Cntr=0.3,0.1

Type RM Length L Ch R = 1 ,7662    ,522.8,519.6,522.2
XS GIS Cut Line= 4
     2035494.291      149668.887     2035289.885      149951.597
     2034734.742      150393.714     2034417.902       150497.88
#Sta/Elev= 30
       0 1860.88    39.1 1846.25    52.2 1843.48    78.2 1834.65    94.6 1831.06
     150 1821.69   198.9 1816.17   270.6 1803.03     300 1800.77   365.2 1796.61
   463.3 1787.46   708.6 1787.35     774 1786.49   796.9 1784.73   801.7 1783.23
   816.5 1782.01   826.4  1782.1   832.9 1783.37   842.7 1786.82   855.8 1786.65
   862.3 1787.69   881.9 1793.49   888.5 1796.65   904.8 1801.82   940.8 1810.78
     967 1816.22  1042.2  1828.2  1071.6 1832.03  1153.4 1840.04  1392.1 1858.94
#Mann= 5 ,-1 , 0
       0      .1       0     300     .05       0   801.7    .045       0
   832.9     .05       0  948.86    .035       0
Bank Sta=801.7,832.9
XS Rating Curve= 0 ,0
Exp/Cntr=0.3,0.1