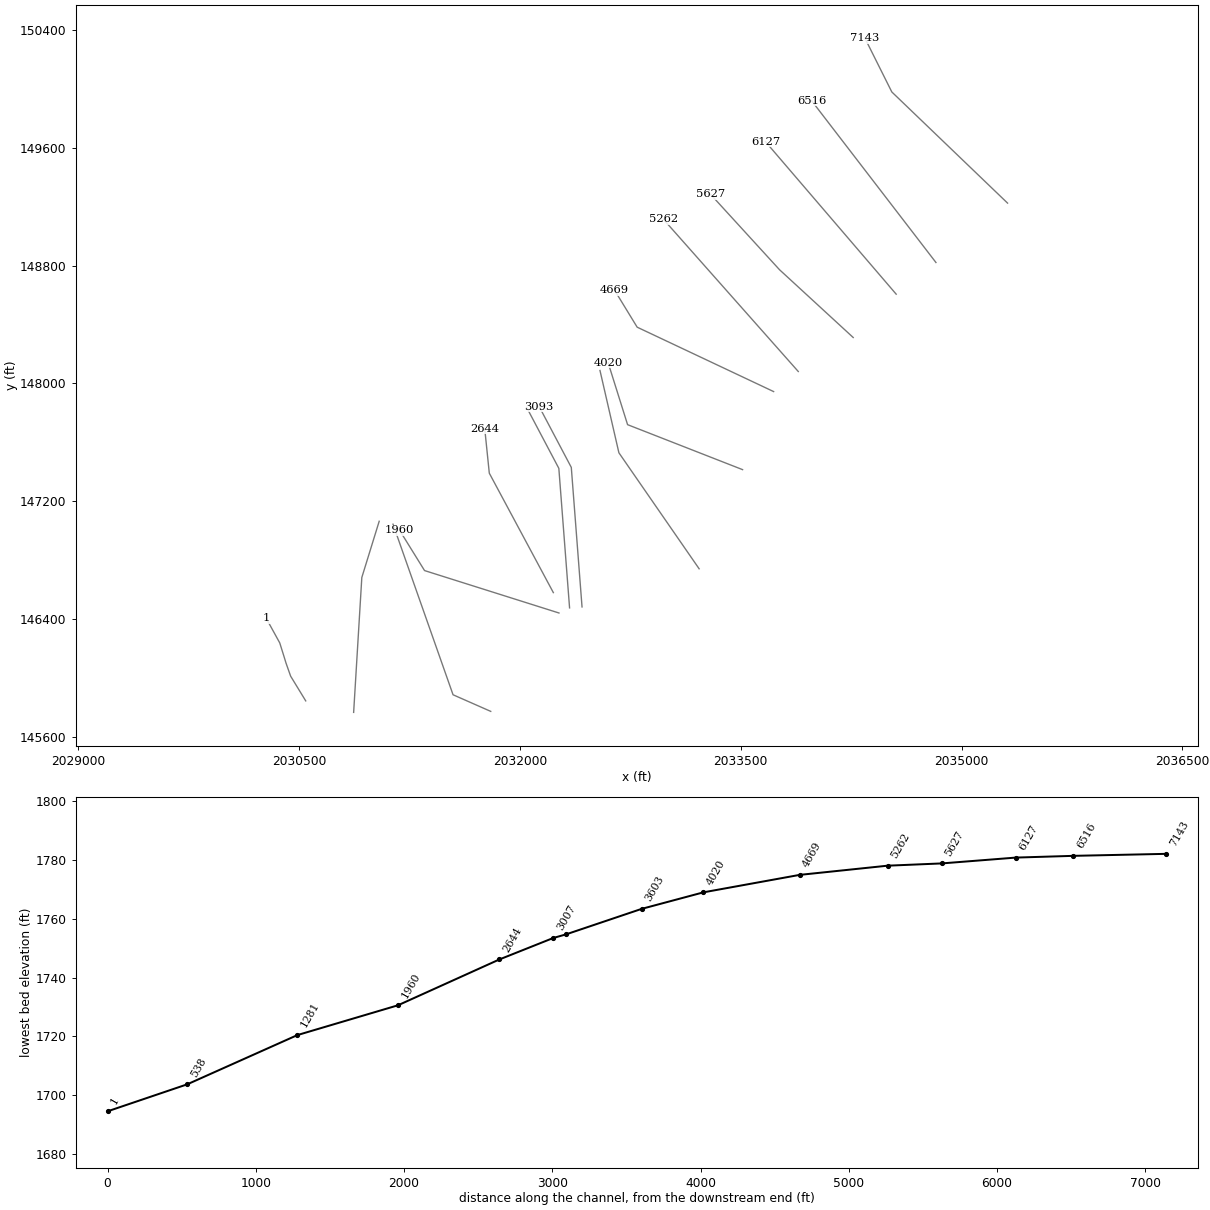
HEC-RAS study RICHCK_A.prj: RICHCK_A

--- RICHCK_A.g01 (geometry) --- (continued)

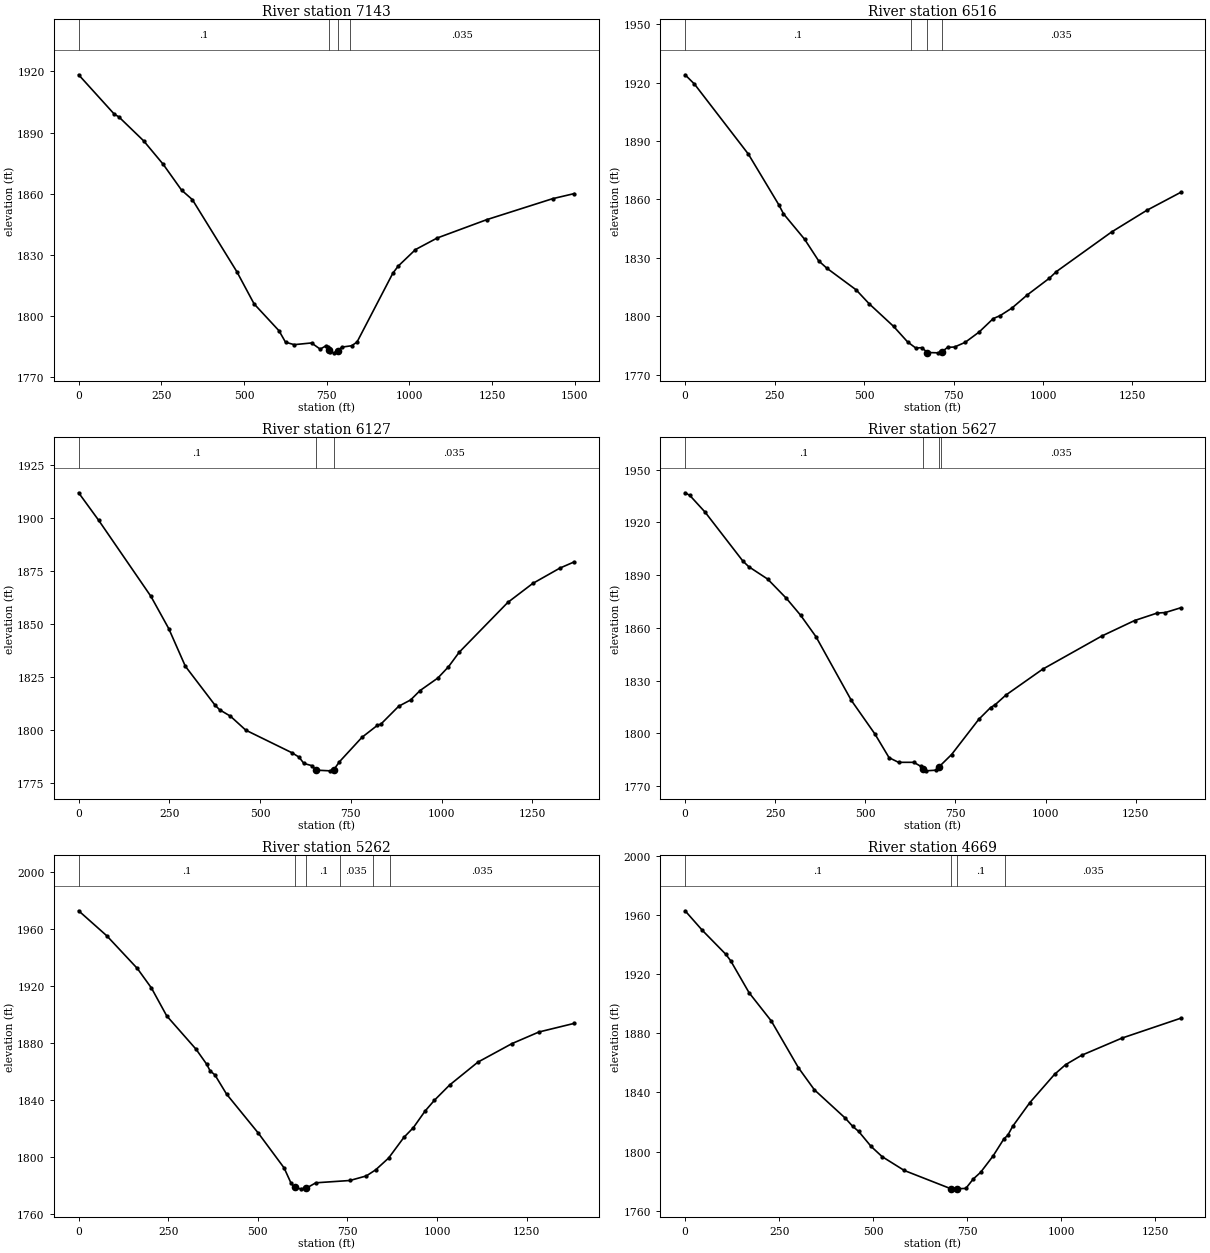
Type RM Length L Ch R = 1 ,7143    ,620.9,627.1,610.3
XS GIS Cut Line= 3
     2035312.867      149224.443     2034526.409      149979.651
     2034344.117      150344.235
#Sta/Elev= 30
       0 1918.37     108 1899.02   121.2 1897.77   196.5 1885.97   255.4  1874.5
   311.1  1861.8   343.8 1857.12     478 1821.85   530.4 1805.98   605.8 1792.78
   625.4 1787.18   651.6 1785.97     704 1786.81   730.2 1783.78   746.5  1785.3
   753.1 1784.96   756.4 1783.58   759.6 1782.37   772.7 1781.96   783.1 1782.95
   795.7 1784.77   825.1 1785.43   841.5 1787.23   949.6 1820.95   965.9 1824.49
  1018.3 1832.62  1083.8 1838.29  1233.8  1847.3  1432.7 1857.58    1498 1860.07
#Mann= 4 ,-1 , 0
       0      .1       0   756.4    .045       0   783.1      .1       0
     820    .035       0
Bank Sta=756.4,783.1
XS Rating Curve= 0 ,0
Exp/Cntr=0.3,0.1

Type RM Length L Ch R = 1 ,6516    ,388.4,388.1,389.4
XS GIS Cut Line= 2
      2034826.31      148820.923     2033982.602       149918.69
#Sta/Elev= 30
       0    1924    26.2 1919.22   176.8 1883.27   261.8 1857.28   274.9 1852.65
   333.9 1839.58   373.1 1828.51     396 1824.73   477.9 1813.61   513.9 1806.53
   582.6 1794.84   621.9 1786.84   644.8 1783.71   661.2 1783.95   677.1 1781.45
     707 1781.28   716.8  1781.7   733.2 1784.07   752.8 1784.28   782.3 1786.64
   821.6 1791.98   860.8 1798.84   880.5 1800.41   913.2 1804.26   955.8 1810.97
  1017.9  1819.6  1037.6 1823.02  1191.4 1843.29  1289.6 1854.39  1384.5 1863.63
#Mann= 4 ,-1 , 0
       0      .1       0     630    .035       0   677.1    .045       0
   716.8    .035       0
Bank Sta=677.1,716.8
XS Rating Curve= 0 ,0
Exp/Cntr=0.3,0.1

Type RM Length L Ch R = 1 ,6127    ,495.1,500,499.4
XS GIS Cut Line= 3
     2034556.083      148605.865     2034111.919      149124.059
     2033667.755      149642.252
#Sta/Elev= 30
       0 1911.82    55.5 1898.77   199.2 1862.95   248.2 1847.77   293.9 1830.04
   375.5 1811.71   388.6 1809.46     418 1806.48   460.4 1799.88   587.8  1789.2
   607.4 1787.13   620.4 1784.18   643.3 1783.09   653.1 1781.03   692.3 1780.69
   702.1 1781.05   718.4 1784.96   780.5  1796.5   822.9 1802.14   832.7 1802.74
   881.7 1811.16   914.4 1814.11   940.5 1818.55   989.5 1824.46  1018.8 1829.77
  1048.2  1836.6  1182.1  1860.1  1250.7 1869.04  1325.8 1876.31    1365 1879.22
#Mann= 3 ,-1 , 0
       0      .1       0   653.1    .045       0   702.1    .035       0
Bank Sta=653.1,702.1
XS Rating Curve= 0 ,0
Exp/Cntr=0.3,0.1

Type RM Length L Ch R = 1 ,5627    ,367.5,365.2,364.3
XS GIS Cut Line= 3
     2034264.174      148311.318     2033763.448       148771.99
      2033294.84      149284.425
#Sta/Elev= 30
       0 1936.83    13.1 1935.33    55.6 1925.79   160.3    1898   176.6  1894.8
     229 1887.76   281.3 1876.74   320.6 1867.15   363.1 1854.98   461.2 1818.78
   526.7 1799.64   565.9 1786.19   592.1 1783.55   634.6 1783.55   654.2 1781.22
   660.8 1779.61   667.3 1778.71   696.8 1779.09   703.3 1780.74   739.4    1788
   814.7 1807.98   847.4 1814.67   860.6 1816.37     890  1821.8   991.6 1836.46
  1155.3 1855.29    1247 1864.18  1309.3 1868.41  1332.2 1868.73  1374.8 1871.42
#Mann= 4 ,-1 , 0
       0      .1       0   660.8    .045       0   703.3      .1       0
   710.4    .035       0
Bank Sta=660.8,703.3
XS Rating Curve= 0 ,0
Exp/Cntr=0.3,0.1

Type RM Length L Ch R = 1 ,5262    ,585.4,593.1,593
XS GIS Cut Line= 2
     2033890.992      148080.346     2032974.326      149115.068
#Sta/Elev= 30
       0 1972.83    78.6 1955.29   163.8 1932.39   203.1 1918.71   245.7 1899.18
   327.6 1875.78   357.1 1865.33   366.9 1860.58     380 1857.86   412.7 1844.34
   501.2 1817.02   573.2  1792.6   592.9 1781.72   602.7 1778.95   619.1 1777.94
   635.5 1778.45   661.7 1782.17   756.7 1783.79   802.6 1786.99   828.8 1791.29
   864.8 1799.53   907.4 1814.02   933.6 1820.77   966.3  1832.4   992.6 1840.04
  1035.1 1850.74  1113.8 1866.75  1208.8 1879.73  1284.1 1887.87  1382.4 1893.91
#Mann= 6 ,-1 , 0
       0      .1       0   602.7    .045       0   635.5      .1       0
     730    .035       0     820      .1       0     870    .035       0
Bank Sta=602.7,635.5
XS Rating Curve= 0 ,0
Exp/Cntr=0.3,0.1

Type RM Length L Ch R = 1 ,4669    ,647.1,648.8,643.3
XS GIS Cut Line= 3
     2033723.457      147944.061     2032796.374      148381.561
     2032643.596      148631.561
#Sta/Elev= 30
       0 1962.73    45.8 1949.53   108.1 1933.38   121.2 1928.96   170.3 1907.31
   229.3 1888.26   301.3 1856.71   343.9 1841.74   425.8 1822.66   445.4 1817.16
   461.8 1813.59   494.6 1803.52     524 1796.59     583 1787.23     707 1774.88
     714 1774.82     722 1774.88   746.7  1775.1   766.4 1781.44     786 1785.97
   818.8 1796.88   848.3 1808.71   858.1 1810.91   871.2 1817.02     917 1833.09
   982.6 1852.17    1012 1858.72  1054.4 1865.04  1161.9 1876.68  1318.1  1890.1
#Mann= 4 ,-1 , 0
       0      .1       0     707    .045       0     722      .1       0
     850    .035       0
Bank Sta=707,722
XS Rating Curve= 0 ,0
Exp/Cntr=0.3,0.1

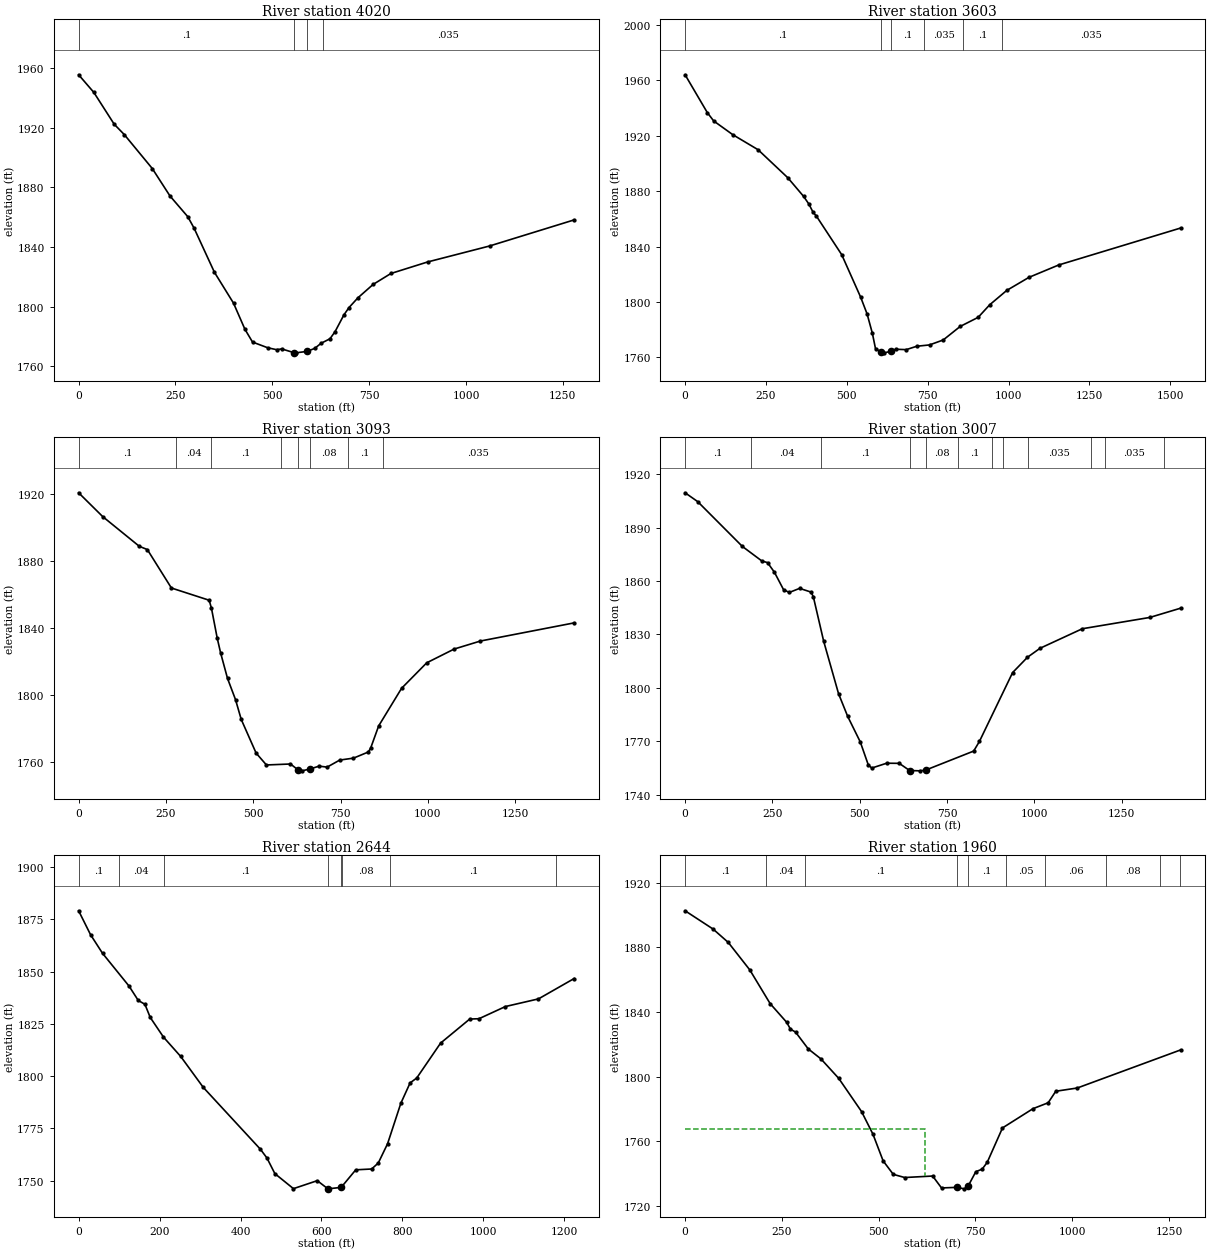
Type RM Length L Ch R = 1 ,4020    ,432.3,416.9,411.1
XS GIS Cut Line= 3
      2033512.52      147413.679      2032731.27      147719.235
     2032599.326      148139.373
#Sta/Elev= 30
       0 1955.54    39.3 1943.69    91.8 1922.36     118 1915.36   190.1 1892.62
   235.9 1874.16   281.8 1860.27   298.2  1852.5   350.6 1822.95   399.8 1802.27
   429.3  1784.7   448.9 1776.14   488.2  1772.3   511.2 1771.01   524.3 1771.53
     556 1769.01   560.3  1768.9   589.8 1769.86   609.5  1771.9   625.9 1775.32
   648.8 1778.34   661.9  1783.1   684.9 1794.42     698 1799.31   720.9 1805.82
   760.2 1814.82   806.1 1822.16   900.9  1829.9  1060.7 1840.61  1279.2 1858.14
#Mann= 4 ,-1 , 0
       0      .1       0     556    .045       0   589.8      .1       0
     630    .035       0
Bank Sta=556,589.8
XS Rating Curve= 0 ,0
Exp/Cntr=0.3,0.1

Type RM Length L Ch R = 1 ,3603    ,521.3,510,500.2
XS GIS Cut Line= 3
     2033217.381      146740.068     2032672.242      147528.262
      2032543.77       148087.29
#Sta/Elev= 30
       0 1964.04    68.7 1936.73    88.3 1930.73   147.2 1920.83   225.7 1909.92
   317.3 1889.75   366.3 1876.26   382.7 1870.71   395.8  1864.7   405.6 1862.13
   484.1 1834.19     543 1803.34   562.6 1791.41   578.9 1777.48   588.7 1766.27
   605.1 1763.86   614.9 1763.29   635.6 1764.35   650.9 1765.89   683.6  1765.6
   716.3 1768.05   755.6    1769   798.1 1772.59   850.4 1782.34     906 1788.91
     942 1798.04   994.4 1808.35  1063.2  1817.8    1155 1826.72    1532  1853.4
#Mann= 6 ,-1 , 0
       0      .1       0   605.1    .045       0   635.6      .1       0
     740    .035       0     860      .1       0  978.35    .035       0
Bank Sta=605.1,635.6
XS Rating Curve= 0 ,0
Exp/Cntr=0.3,0.1

Type RM Length L Ch R = 1 ,3093    ,86,86.2,89.1
XS GIS Cut Line= 3
     2032421.808      146480.953     2032348.892       147428.87
     2032130.447      147842.591
#Sta/Elev= 30
       0 1920.81    68.8  1906.6   173.8 1888.81   196.7 1886.87   265.6  1863.9
   373.7 1856.59   380.3 1851.76   396.7 1833.98   406.5 1825.08   426.2 1809.88
   449.1 1797.21   465.5 1785.36   508.1 1765.24   537.6 1758.15   606.5 1758.73
   629.4 1755.02   639.3 1754.64   662.2 1755.74   688.4 1757.44   711.4 1756.87
   747.5 1761.08   786.8 1762.23   829.4  1765.9     836 1768.23   858.9 1781.48
   924.5 1803.96   996.5  1819.2    1075 1827.42  1150.3 1832.22  1418.6 1843.06
#Mann= 8 ,-1 , 0
       0      .1       0     280     .04       0     380      .1       0
     580     .08       0   629.4    .045       0   662.2     .08       0
     770      .1       0     870    .035       0
Bank Sta=629.4,662.2
XS Rating Curve= 0 ,0
Exp/Cntr=0.3,0.1

Type RM Length L Ch R = 1 ,3007    ,354.2,363.4,370.6
XS GIS Cut Line= 3
     2032337.173      146474.443     2032264.256       147422.36
     2032045.812       147836.08
#Sta/Elev= 30
       0  1909.6    36.1 1904.63   163.9 1879.47   219.6 1871.31     236 1870.37
   255.7 1864.97   281.9 1855.16   298.3 1853.62   327.8  1855.9   360.6 1853.82
   367.2 1851.13   396.7 1826.22   439.3 1796.74   465.5 1783.97   501.6  1769.6
   524.5 1756.71   534.4 1754.98     577 1757.69     613 1757.62   642.6  1753.6
   672.1 1753.41   688.4 1753.81   826.1 1764.51   842.5  1769.9   937.6  1808.6
   980.2 1817.22  1016.2 1822.26  1137.2 1833.23  1330.2 1839.57  1418.6 1844.78
#Mann= 12 ,-1 , 0
       0      .1       0     190     .04       0     390      .1       0
   642.6    .045       0   688.4     .08       0     780      .1       0
     880    .035       0     910      .1       0  980.72    .035       0
 1160.72      .1       0 1200.72    .035       0 1370.72      .1       0
Bank Sta=642.6,688.4
XS Rating Curve= 0 ,0
Exp/Cntr=0.3,0.1

Type RM Length L Ch R = 1 ,2644    ,668.8,684.1,699.4
XS GIS Cut Line= 3
       2032226.9      146578.228     2031791.817       147389.59
     2031760.814      147691.838
#Sta/Elev= 30
       0 1879.15    29.5 1867.69      59 1858.82   124.5 1843.14   147.4 1836.24
   163.8 1834.42   176.9 1828.14   209.7 1818.71   252.3 1809.44     308 1794.66
   448.9 1765.13   465.2 1760.93   484.9 1753.41   530.8 1746.22   589.7 1750.04
     616 1746.13   648.7 1746.82   684.8 1755.23   724.1 1755.62   740.5 1758.51
   763.4  1767.7   796.2 1787.07   819.1 1796.81   835.5 1799.16   894.4 1815.84
   966.4 1827.35   989.3 1827.51  1054.6 1833.34  1136.3    1837  1224.5 1846.75
#Mann= 8 ,-1 , 0
       0      .1       0     100     .04       0     210      .1       0
     616    .045       0   648.7      .1       0     650     .08       0
     770      .1       0 1180.65    .035       0
Bank Sta=616,648.7
XS Rating Curve= 0 ,0
Exp/Cntr=0.3,0.1

Type RM Length L Ch R = 1 ,1960    ,698.3,678.6,669.7
XS GIS Cut Line= 3
     2032265.124      146439.721      2031351.93      146727.915
     2031182.008      147002.004
#Sta/Elev= 30
       0 1902.55    72.2 1891.26   111.5 1882.98   167.2 1865.96   219.7 1845.13
   262.4 1833.58   272.2 1829.32   285.3 1827.54   318.1 1817.13   350.9 1810.95
   396.8 1798.93   455.8 1778.38   485.4 1764.31   511.6 1747.86   537.8 1739.53
   567.3 1737.58   639.5  1738.5   662.4 1731.13   701.4 1731.49   721.5 1730.58
   731.3 1732.35     751 1741.19   767.4 1742.76   780.5    1747   819.9 1768.25
   898.6 1780.15   937.9 1783.81   957.6 1790.94    1013 1792.94  1280.1  1816.5
#Mann= 10 ,-1 , 0
       0      .1       0     210     .04       0     310      .1       0
   701.4    .045       0   731.3      .1       0     830     .05       0
     930     .06       0 1087.59     .08       0 1227.59     .06       0
 1277.59     .08       0
#XS Ineff= 2 , 0
          620.46 1767.86
Permanent Ineff=
       F       F
Bank Sta=701.4,731.3
XS Rating Curve= 0 ,0
Exp/Cntr=0.3,0.1

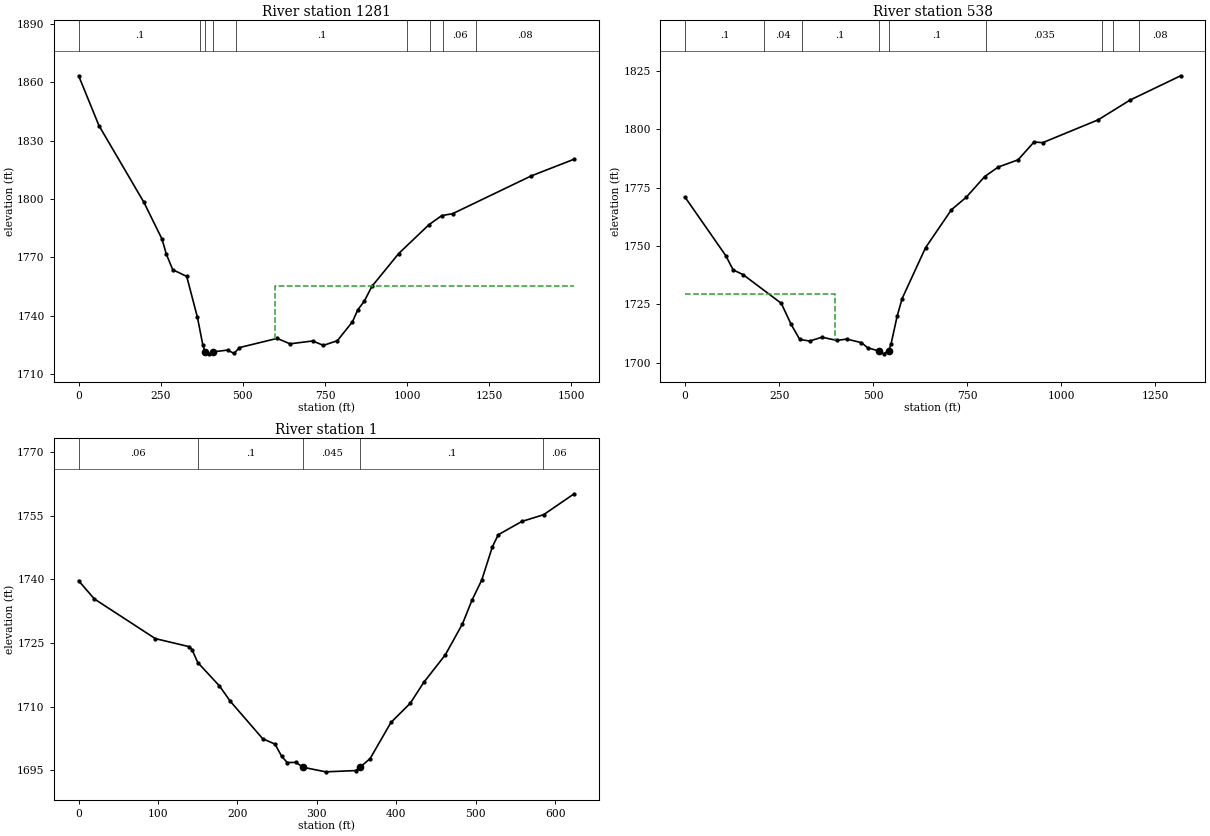
Type RM Length L Ch R = 1 ,1281    ,746.6,742.7,738.7
XS GIS Cut Line= 3
     2031801.582      145771.318     2031545.506      145884.165
      2031137.52      147043.019
#Sta/Elev= 30
       0 1863.33    61.8 1837.75   198.5 1798.37   253.8 1779.44   266.8 1771.76
   286.4  1763.7     329 1760.25   361.7 1739.17   378.1 1724.99   384.7 1721.66
   397.8 1720.47   409.9 1721.48   453.5 1722.41   473.1 1720.68   489.5 1723.68
   604.2 1728.41   643.5 1725.62   712.3 1727.08   745.1 1724.82   787.6 1727.23
   833.5 1736.94   849.9 1743.16   869.6 1747.52   892.5 1755.09   974.4 1772.02
  1066.1 1786.78  1105.4 1791.51  1138.2 1792.46  1377.4 1811.86  1508.4 1820.48
#Mann= 9 ,-1 , 0
       0      .1       0  369.84     .04       0   384.7    .045       0
   409.9     .04       0  479.84      .1       0  999.84     .05       0
 1069.84     .03       0 1109.84     .06       0 1209.84     .08       0
#XS Ineff= 2 , 0
                          598.76         1755.24
Permanent Ineff=
       F       F
Bank Sta=384.7,409.9
XS Rating Curve= 0 ,0
Exp/Cntr=0.3,0.1

Type RM Length L Ch R = 1 ,538     ,534,537.6,541.3
XS GIS Cut Line= 3
     2030870.159      145764.373     2030925.714       146681.04
      2031043.77      147062.985
#Sta/Elev= 30
       0 1770.85   108.2 1745.82   127.9 1739.72   154.2 1737.71   255.8 1725.42
   282.1 1716.37     305 1709.92   331.3 1709.26   364.1 1710.89   403.4 1709.52
   429.7 1710.09     469 1708.58   485.4 1706.39   514.9    1705     528 1703.77
   541.2 1705.13   547.7 1707.92   564.1 1719.94   577.2 1727.42   639.6 1749.24
   708.4 1765.49   747.8 1770.84     797 1779.72   833.1  1783.8   885.6 1786.87
   928.2 1794.53   951.1 1794.22  1098.6    1804  1183.8 1812.49  1318.1 1822.88
#Mann= 9 ,-1 , 0
       0      .1       0     210     .04       0     310      .1       0
   514.9    .045       0   541.2      .1       0     800    .035       0
 1108.35     .04       0 1138.35     .06       0 1208.35     .08       0
#XS Ineff= 2 , 0
          398.31  1729.2
Permanent Ineff=
       F       F
Bank Sta=514.9,541.2
XS Rating Curve= 0 ,0
Exp/Cntr=0.3,0.1

Type RM Length L Ch R = 1 ,1       ,,5.1,
XS GIS Cut Line= 6
     2030544.531      145842.657     2030442.103       146010.57
     2030411.062      146098.338      2030397.52      146142.623
     2030368.069      146236.649     2030276.815      146402.579
#Sta/Elev= 30
       0 1739.63    19.8 1735.35    96.6    1726   138.9 1724.12   142.8 1723.38
     150 1720.37   177.3 1714.86   191.1 1711.21   231.8 1702.41   247.3 1701.14
   255.7 1698.25   262.7  1696.8   273.5 1696.84   282.8 1695.68   311.1 1694.61
   348.9 1694.91   354.4 1695.68   367.1 1697.75   393.3 1706.25   417.6 1710.77
   434.6 1715.69   461.7 1722.17   483.3 1729.46   495.5 1735.14   507.6 1739.79
     521 1747.63   528.4 1750.48   558.1 1753.61   585.4 1755.19     624 1760.13
#Mann= 5 ,-1 , 0
       0     .06       0     150      .1       0   282.8    .045       0
   354.4      .1       0  584.62     .06       0
Bank Sta=282.8,354.4
XS Rating Curve= 0 ,0
Exp/Cntr(USF)=0,0
Exp/Cntr=0.3,0.1
LCMann Table=0

Chan Stop Cuts=-1
Use User Specified Reach Order=0
Composite Channel Slope=5